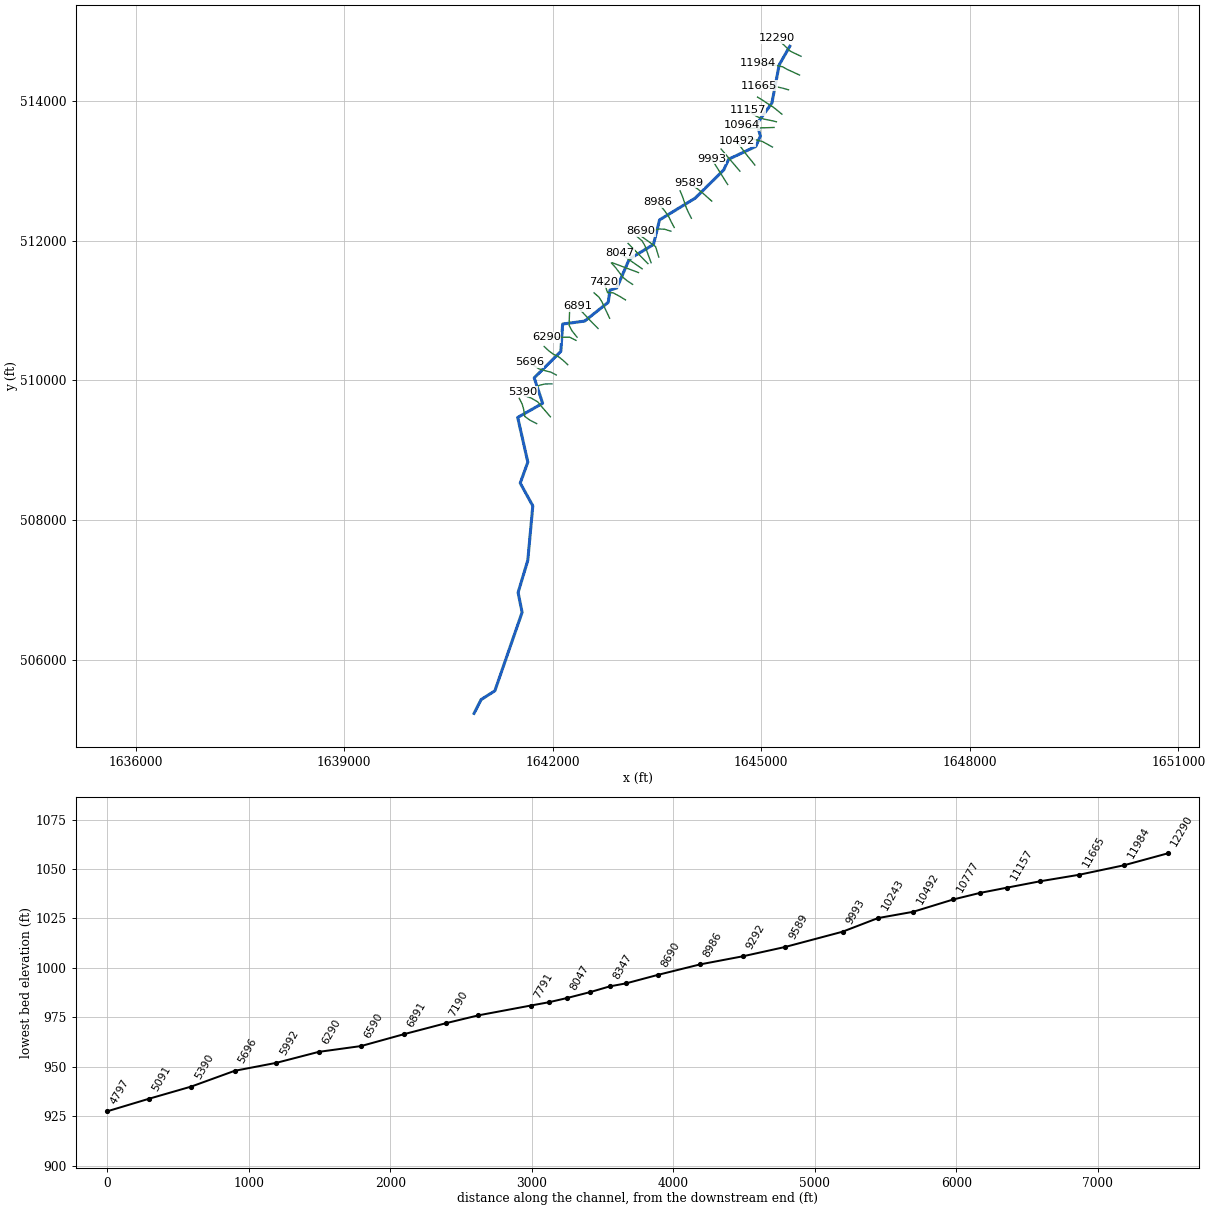
--- NFMidGraveCk.prj (project) ---

Proj Title=NFMidGraveCk
Current Plan=p01
Default Exp/Contr=0,0
English Units
Geom File=g01
Flow File=f01
Plan File=p01
BEGIN DESCRIPTION:
---------- MODELED AS PART OF WVEM CTP PROGRAM, 2025----------
Stream Name: North Fork Middle Grave Creek
Flood Zone: AFH
Marshall County, WV
HEC-RAS Version: RAS 6.6
Vertical Datum: NAVD88
Projection: NAD 1983 StatePlane West Virginia N FIPS 4701 (US Feet)
Terrain: 1-meter West Virginia FEMA R3 South Central (collected 2018-2019)
Land Use: 2024 NLCD
Hydrologic Method:
Duda et al., "Estimation of magnitude and frequency of floods for rural, unregulated streams in and near Virginia and West Virginia." September 8, 2025.
Additional Model Notes:
None
END DESCRIPTION:
DSS Export Rating Curves= 0
DSS Export Rating Curve Sorted= 0
DSS Export Volume Flow Curves= 0
DXF OffsetX= 0
DXF OffsetY= 0
DXF ScaleX= 0
DXF ScaleY= 0

--- NFMidGraveCk.p01 (plan) ---

Plan Title=Floodplain
Program Version=6.60
Short Identifier=Floodplain
Geom File=g01
Flow File=f01
Subcritical Flow
K Sum by GR= 0
Std Step Tol= 0.01
Critical Tol= 0.01
Num of Std Step Trials= 20
Max Error Tol= 0.3
Flow Tol Ratio= 0.001
Split Flow NTrial= 30
Split Flow Tol= 0.02
Split Flow Ratio= 0.02
Log Output Level= 0
Friction Slope Method= 1
Unsteady Friction Slope Method= 2
Unsteady Bridges Friction Slope Method= 1
Parabolic Critical Depth
Global Vel Dist= 0 , 0 , 0
Global Log Level= 0
CheckData=False
Encroach Param=-1 ,0,0, 0
Flow Ratio Tolerance=0.1
Flow Ratio Min Ratio=0.5
Flow Ratio Max Ratio=4
Flow Ratio Max Iterations= 10
Mapping Interval=1HOUR
Computation Time Step Use Courant=        0
Computation Time Step Use Time Series=    0
Computation Time Step Count To Double=0
Computation Time Step Max Doubling=0
Computation Time Step Max Halving=0
Computation Time Step Residence Courant=0
Run HTab= 0
Run UNet= 0
Run Sediment= 0
Run PostProcess= 0
Run WQNet= 0
Run RASMapper=-1
UNET Theta= 0
UNET Theta Warmup= 0
UNET ZTol= 0
UNET ZSATol= 0
UNET MxIter= 0
UNET Max Iter WO Improvement= 0
UNET MaxInSteps= 0
UNET DtIC= 0
UNET DtMin= 0
UNET MaxCRTS= 0
UNET WFStab= 0
UNET SFStab= 0
UNET WFX= 1
UNET SFX= 1
UNET Gravity=32.17405
UNET 1D Methodology=Finite Difference
UNET DSS MLevel= 1
UNET Pardiso=0
UNET DZMax Abort= 0
UNET Use Existing IB Tables= 0
UNET Froude Reduction=False
UNET Froude Limit= 0
UNET Froude Power= 0
UNET D1 Cores= 0
UNET WindReference=Eulerian
UNET WindDragFormulation=Hsu (1988)
UNET D2 Coriolis=0
UNET D2 Cores= 0
UNET D2 Theta= 1
UNET D2 Theta Warmup= 1
UNET D2 Z Tol= 0.01
UNET D2 Volume Tol= 0.01
UNET D2 Max Iterations= 20
UNET D2 Advanced Convergence=0
UNET D2 WS Max Tol=0.15
UNET D2 WS RMS Tol=0.002
UNET D2 WS Stall Tol=1
UNET D2 Equation= 0
UNET D2 RampUpFraction=0.1
UNET D2 TimeSlices= 1
UNET D2 Turbulence Formulation=Non-Conservative (original)
UNET D2 Eddy Viscosity=0.3
UNET D2 Transverse Eddy Viscosity=0.1
UNET D2 Smagorinsky Mixing=0
UNET D2 BCVolumeCheck=0
UNET D2 Cores=0
UNET D2 SolverType=PARDISO (Direct)
UNET D2 Minimum Iterations= 3
UNET D2 Maximum Iterations= 30
UNET D2 Restart Number= 10
UNET D2 Relaxation Coeff=1.3
UNET D2 SOR Precondition Iterations= 10
UNET D2 ILUT Maximum Fill= 8
UNET D2 ILUT Tolerance=1E-08
UNET D2 Convergence Tolerance=0.00001
PS Theta= 1
PS WS Tol= 0.01
PS Volume Tol= 0.01
PS Max Iterations= 20
PS Equation= 0
PS Advance Time Step=-1
PS Target Courant=0.9
PS Time Slices= 1
PS Iterate With 2D=0
PS Project Initial WSE from DS=-1
PS Ramp Up Initial WSE from US=-1
PS Cores=0
UNET D1D2 MaxIter= 0
UNET D1D2 ZTol=0.01
UNET D1D2 QTol=0.1
UNET D1D2 MinQTol=1
Write IC File= 0
Write IC File at Fixed DateTime=0
Write IC File at Sim End=0
Echo Input=False
Echo Parameters=False
Echo Output=False
Write Detailed= 0
HDF Write Warmup=0
HDF Write Time Slices=0
HDF Flush=0
HDF Compression= 1
HDF Chunk Size= 1
HDF Spatial Parts= 1
HDF Use Max Rows=0
HDF Fixed Rows= 1
Calibration Method= 0
Calibration Iterations= 20
Calibration Max Change=0.05
Calibration Tolerance=0.2
Calibration Maximum=1.5
Calibration Minimum=0.5
Calibration Optimization Method= 1
WQ AD Non Conservative
WQ ULTIMATE=-1
WQ Max Comp Step=1HOUR
WQ Output Interval=15MIN
WQ Output Selected Increments= 0
WQ Create Restart=0
WQ Fixed Restart=0
WQ System Summary=0
WQ Write To DSS=0
Sorting and Armoring Iterations= 10
XS Update Threshold= 0.02
Bed Roughness Predictor= 0
Processes Affected by Predictor=Sediment Only
Hydraulics Update Threshold= 0.02
Energy Slope Method= 1
Volume Change Method= 1
Sediment Retention Method= 0
Sediment TS Multiplier= 1
Warm Up Method= 0
XS Weighting Method= 0
Number of US Weighted Cross Sections= 1
Number of DS Weighted Cross Sections= 1
Upstream XS Weight=0
Main XS Weight=1
Downstream XS Weight=0
Number of DS XS's Weighted with US Boundary= 1
Upstream Boundary Weight= 1
Weight of XSs Associated with US Boundary= 0
Number of US XS's Weighted with DS Boundary= 1
Downstream Boundary Weight= 0.5
Weight of XSs Associated with DS Boundary= 0.5
Percentile Method= 0
Sediment Output Level= 3
Mass or Volume Output= 0
Output Increment Type= 1
Profile and TS Output Increment= 1
Transport Output Increment 1
XS Output Flag= 0
XS Output Increment= 10
Read HDF5 Sediment Hotstart= 0
Sediment Hotstart Type= 0
Write Gradation File= 0
Read Gradation Hotstart= 0
Write HDF5 File= 1
Write Binary Output= 1
Write DSS Sediment File= 0
DSS Sediment Output Type= 1
SV Curve= 0
Specific Gage Flag= 0
Subcell Erosion Methods= 0
Subcell Deposition Methods= 0
Advection Scheme= 1
Matrix Solver= 0
Implicit Weighting Factor= 1
Maximum Outer Loop Convergence Iterations= 5
Convergence Maximum Absolute= 0.001
Convergence RMSE= 0.0001
Grain Fractions Max Abs Error= 0.001
Max Subgrid Regions= 1
Max Subgrid Length Scale= 3.402823E+38
Initial Layer Thickness= 3
Min Layer Thickness= 0.1
Max Layer Thickness= 6
Number of Layers= 5

--- NFMidGraveCk.f01 (steady flow) ---

Flow Title=Flow
Program Version=6.60
Number of Profiles= 1
Profile Names=P100yr
River Rch & RM=NFMidGraveCk,Main,12290
     956
River Rch & RM=NFMidGraveCk,Main,8690
    1030
River Rch & RM=NFMidGraveCk,Main,6590
    1220
River Rch & RM=NFMidGraveCk,Main,901
    1230
Boundary for River Rch & Prof#=NFMidGraveCk,Main            , 1
Up Type= 0
Dn Type= 3
Dn Slope=0.038729
DSS Import GetInterval= 0
DSS Import GetPeak= 0
DSS Import FillOption= 0

--- NFMidGraveCk.g01 (geometry) ---

Geom Title=Geometry
Program Version=6.60

River Reach=NFMidGraveCk    ,Main
Reach XY= 30
      1645411.13      514782.096     1645258.179      514515.864
     1645153.137      513968.811     1644937.414      513673.874
     1644987.751      513498.339      1644921.84      513347.968
     1644531.042      513164.539     1644459.695      513010.785
     1644048.835      512606.614     1643536.904      512296.022
     1643449.479      511943.845     1643102.132      511734.901
      1642921.55       511321.28     1642824.076      511291.304
      1642798.75      511115.787     1642459.261      510846.992
     1642142.754      510804.744     1642117.152       510413.91
     1641734.168      510034.261     1641855.117       509670.39
     1641496.406      509467.535     1641641.992      508828.243
     1641532.941       508528.01     1641713.672      508201.563
     1641641.538       507421.42     1641502.143      506960.508
     1641559.775       506677.28     1641167.845      505554.017
      1640970.33      505428.343     1640868.542      505230.833

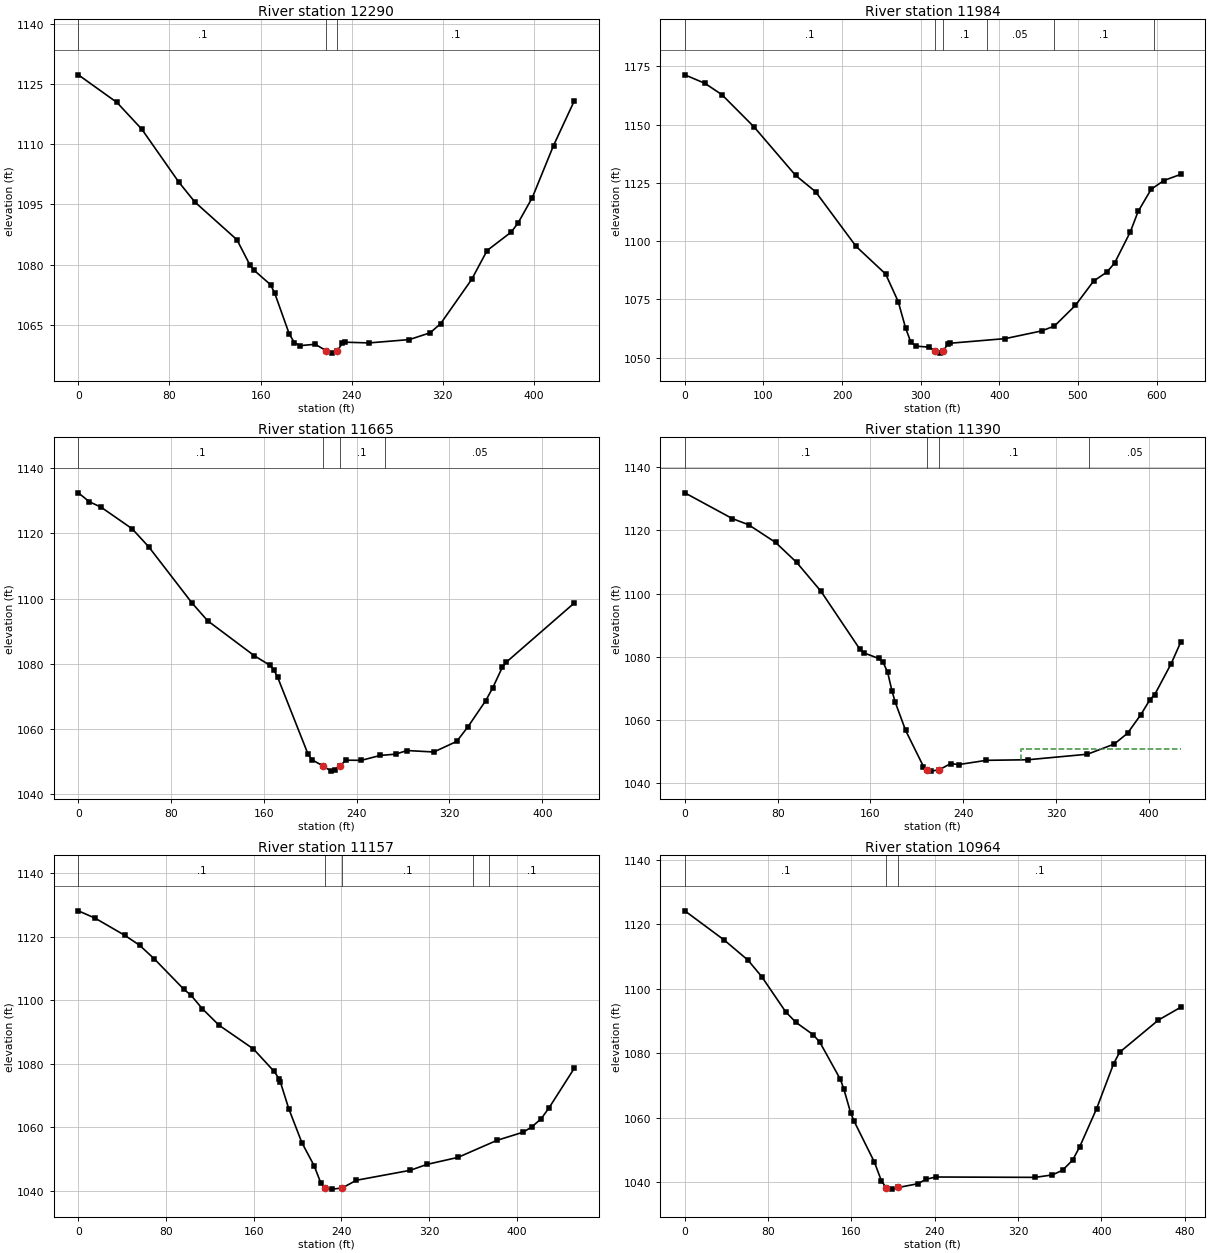
Type RM Length L Ch R = 1 ,12290   ,302.5,306.5,308.4
XS GIS Cut Line= 6
1645571.35341026514638.6645898371645486.07930259514678.696005836
1645415.60733068514713.3068290051645343.52479768514782.618698254
1645289.46092942514834.6002215891645226.38690859514895.246425763
#Sta/Elev= 30
       0 1127.34    33.9 1120.44    55.7 1113.77    88.3 1100.52   102.4 1095.56
   139.2 1086.18   150.4 1079.99     154 1078.62   168.7 1074.96   172.3  1072.9
   185.1 1062.68   189.7 1060.46     195 1059.76   207.9 1060.09   217.71058.466
   222.3 1057.88   227.41058.472   231.5 1060.29   233.8 1060.61   255.2 1060.43
   290.6 1061.26   308.8 1062.96   317.9  1065.2   345.2 1076.26   358.8 1083.49
     380  1088.1   386.1 1090.42   398.5 1096.72   417.1  1109.7   435.2 1120.77
#Mann= 3 ,-1,0
       0      .1       0   217.7    .045       0   227.4      .1       0
Bank Sta=217.7,227.4
XS Rating Curve= 0 ,0
Exp/Cntr(USF)=0,0
Exp/Cntr=0.3,0.1

Type RM Length L Ch R = 1 ,11984   ,317.3,319.4,320.1
XS GIS Cut Line= 6
1645551.07097048514369.643146232 1645373.2714573514450.504533067
1645304.88609539514488.6714514791645206.38530813514507.735717803
 1645131.7581608514515.2081438151644952.60464773514544.467271641
#Sta/Elev= 30
       0 1171.37    25.7  1167.7    47.2 1162.84    88.1 1148.99   140.8 1128.24
   166.3 1121.19   217.8 1097.73   255.4 1085.86   271.4    1074   280.8 1062.67
   287.5 1056.54   294.2  1054.9   310.9 1054.48   317.6 1052.79   324.3 1051.91
   328.5 1052.83   334.3 1055.69   337.6 1056.16   407.6 1058.15   453.6 1061.43
   470.1 1063.55   496.7 1072.41   519.9 1082.86   536.6 1086.67   546.5 1090.54
   566.5 1103.94   576.5 1112.75   593.1 1122.28   609.3 1126.01   630.5 1128.63
#Mann= 6 ,-1,0
       0      .1       0   317.6    .045       0   328.5      .1       0
  383.99     .05       0  468.99      .1       0  596.64     .05       0
Bank Sta=317.6,328.5
XS Rating Curve= 0 ,0
Exp/Cntr(USF)=0,0
Exp/Cntr=0.3,0.1

Type RM Length L Ch R = 1 ,11665   ,276.7,274.5,270.3
XS GIS Cut Line= 6
1645392.21630134514157.8616584631645307.12657651514182.428538466
1645233.20808917514198.8218783831645133.21977209514200.770037213
1645058.15889859514206.3048030531644970.68007092 514214.93044197
#Sta/Elev= 30
       0 1132.46     9.4 1129.75    19.7 1128.03    46.4 1121.43    60.7 1115.89
    98.1 1098.62   111.5  1093.2   151.8 1082.46   165.3 1079.52   168.5 1078.18
   171.8 1075.91   198.1 1052.24   201.4 1050.55     2111048.665   217.8 1047.07
     221 1047.33   225.31048.642   230.9 1050.43     244 1050.38   260.4 1051.89
   273.6 1052.28   283.4 1053.39   306.5 1052.94   326.2 1056.18   336.1 1060.75
   351.3 1068.73   357.3 1072.63   365.7 1079.04     369  1080.5   427.5 1098.62
#Mann= 4 ,-1,0
       0      .1       0     211    .045       0   225.3      .1       0
  264.28     .05       0
Bank Sta=211,225.3
XS Rating Curve= 0 ,0
Exp/Cntr(USF)=0,0
Exp/Cntr=0.3,0.1

Type RM Length L Ch R = 1 ,11390   ,231.4,233.2,234.7
XS GIS Cut Line= 6
1645296.91793551513809.5927571651645229.24024934513865.356425166
  1645170.187874513911.7752955851645085.37636384513964.974336177
1645023.02707909514007.5835029181644947.09317584 514053.75073342
#Sta/Elev= 30
       0 1131.89      41 1123.73      55 1121.78    78.3 1116.17    96.4 1109.86
   117.3 1100.75   150.7 1082.48   154.8 1081.17     167 1079.47   170.9 1078.27
   174.8 1075.08   178.6 1069.12   181.4 1065.56   190.3 1056.68   205.7 1045.24
   208.41044.262   212.4  1043.8   219.31044.245     229 1046.15   236.2 1045.89
     260 1047.22   295.7  1047.4     347 1049.15   370.1 1052.37   381.6 1055.81
   393.1 1061.72   400.8 1066.39     405 1068.04   419.1 1077.78   427.3 1084.54
#Mann= 4 ,-1,0
       0      .1       0   208.4    .045       0   219.3      .1       0
  348.44     .05       0
#XS Ineff= 2 , 0
                          289.71         1050.66
Permanent Ineff=
       F       F
Bank Sta=208.4,219.3
XS Rating Curve= 0 ,0
Exp/Cntr(USF)=0,0
Exp/Cntr=0.3,0.1

Type RM Length L Ch R = 1 ,11157   ,189.8,193.2,194
XS GIS Cut Line= 6
1645217.75559418513700.7334092851645122.42015493513722.782905861
1645036.89801626513739.3721115281644937.98056318513774.490151524
  1644875.669008513816.2935456181644803.24133134513865.463722869
#Sta/Elev= 30
       0 1128.07    15.4 1125.75    42.4 1120.36    55.9 1117.25    69.3 1112.97
    96.3 1103.41     103 1101.46     113 1097.36   128.3 1092.14   159.8 1084.65
   178.7 1077.58   183.2 1075.32   184.3 1074.35     192 1065.91     204  1055.2
   215.2 1047.94   221.4 1042.43   224.9    1041   231.8 1040.59   240.8 1040.95
   253.7 1043.37     303 1046.51   318.1 1048.36   346.5 1050.57   382.1 1055.93
   405.9 1058.48   413.8 1060.13   422.5 1062.75   429.7  1066.2   452.5 1078.52
#Mann= 5 ,-1,0
       0      .1       0   224.9    .045       0   240.8      .1       0
  359.93     .05       0  374.97      .1       0
Bank Sta=224.9,240.8
XS Rating Curve= 0 ,0
Exp/Cntr(USF)=0,0
Exp/Cntr=0.3,0.1

Type RM Length L Ch R = 1 ,10964   ,188.7,187,185.6
XS GIS Cut Line= 3
1645184.61490438513619.3053649521644807.54341357513606.630692992
1644717.76448719513647.823376863
#Sta/Elev= 30
       0 1124.23    37.7  1115.2    60.7 1108.92    73.8 1103.84    96.8 1092.93
   106.6 1089.66   123.1 1085.84   129.6 1083.51   149.3 1072.01   152.6 1069.07
   159.2 1061.62   162.4 1059.08   182.1 1046.25   188.7 1040.54  193.141038.404
   198.6  1037.9   205.1 1038.41   224.2  1039.6   231.4 1040.96   241.2 1041.66
   336.4 1041.55   352.8  1042.3   362.7 1043.75   372.5 1046.94   379.3 1051.11
   395.4 1062.85   411.8 1076.85   417.6 1080.37   454.7 1090.33   476.1  1094.3
#Mann= 3 ,-1,0
       0      .1       0  193.14    .045       0   205.1      .1       0
Bank Sta=193.14,205.1
XS Rating Curve= 0 ,0
Exp/Cntr(USF)=0,0
Exp/Cntr=0.3,0.1

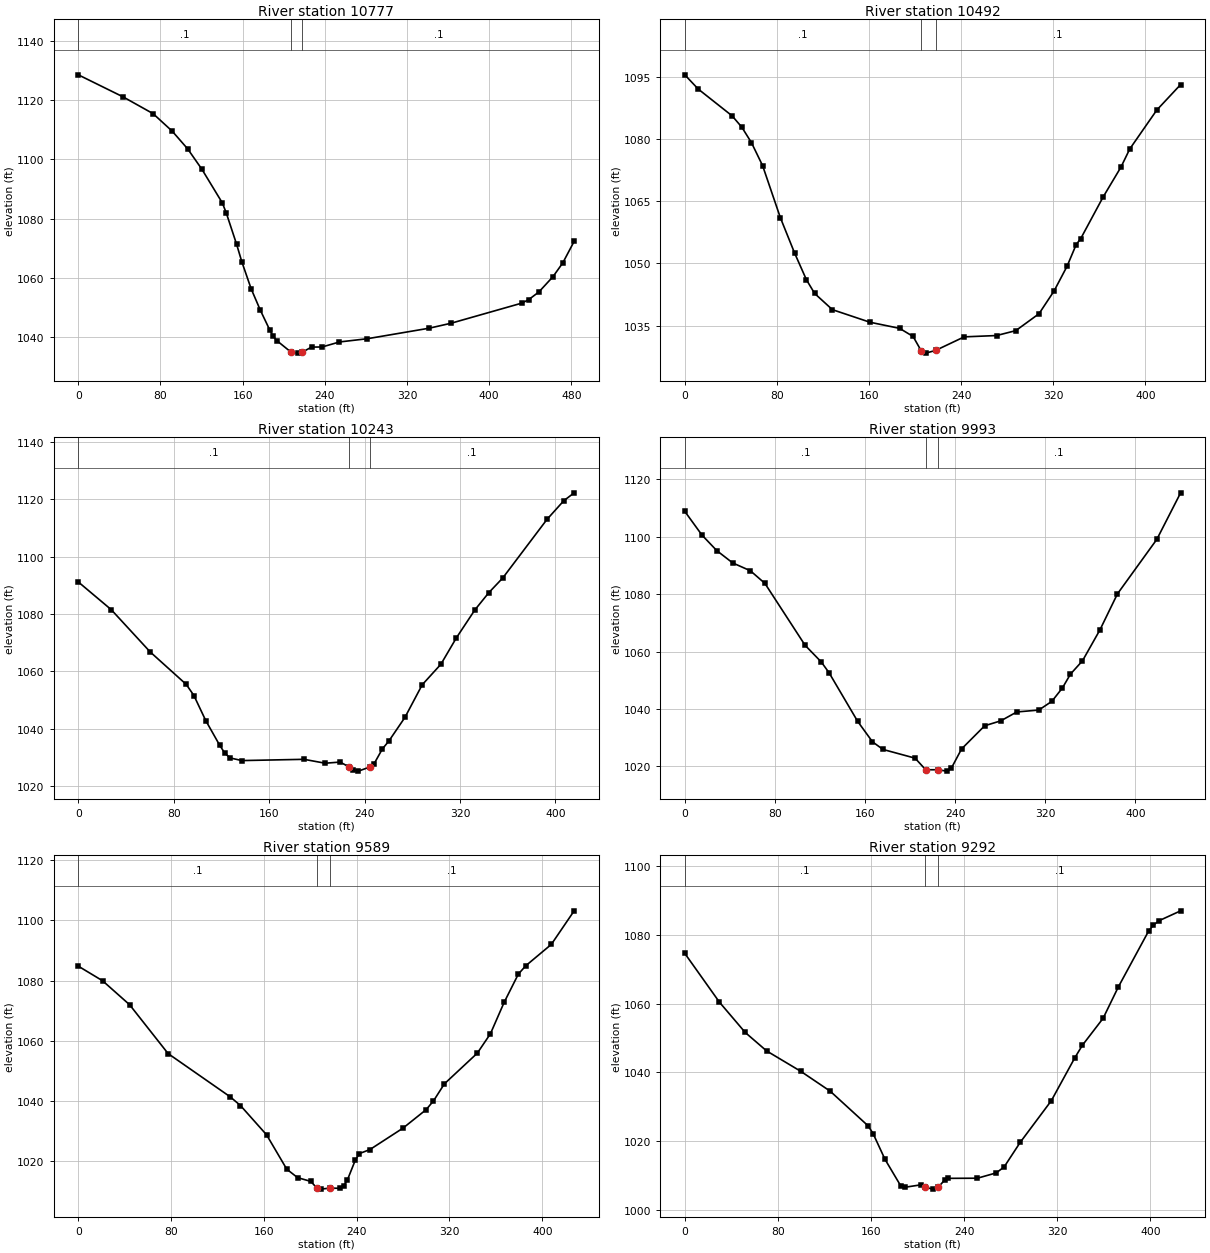
Type RM Length L Ch R = 1 ,10777   ,287.5,284.5,281.1
XS GIS Cut Line= 6
1645161.43821959513338.7875964191645084.82616809513381.045714006
1645019.18292667513417.3189354241644880.64878459513453.571453381
1644837.25872058513461.1039285091644706.26494699513484.242666701
#Sta/Elev= 30
       0 1128.52    43.4 1121.11    72.8 1115.42    91.5 1109.48   106.5 1103.52
   120.3 1096.67   140.2 1085.31     144 1081.97   154.1 1071.36   159.2 1065.44
   168.3  1056.3   177.3 1049.04   186.4 1042.43   189.8 1040.28   193.2 1038.86
   207.11034.951   213.6 1034.62  218.131034.966   227.1 1036.66   237.3 1036.69
   254.3 1038.39   281.4 1039.48   341.8 1043.04   363.1 1044.72   431.7 1051.48
   438.4 1052.64   448.4 1055.24   462.2 1060.43   471.7 1065.05   482.8 1072.34
#Mann= 3 ,-1,0
       0      .1       0   207.1    .045       0  218.13      .1       0
Bank Sta=207.1,218.13
XS Rating Curve= 0 ,0
Exp/Cntr(USF)=0,0
Exp/Cntr=0.3,0.1

Type RM Length L Ch R = 1 ,10492   ,248.7,249,251.5
XS GIS Cut Line= 6
1644908.00237475513081.5751843451644853.44605343513149.982527837
1644805.59378693 513207.733396591644744.48925035513287.010797083
1644699.64321142513349.5756325871644650.56522559513426.411436915
#Sta/Elev= 30
       0 1095.46    11.7 1092.02    41.1 1085.57    49.5 1082.85    57.9 1079.11
    67.6 1073.56      83 1061.03    95.4 1052.48   105.7 1046.03   112.8 1042.75
   128.2 1038.85   160.8 1035.82   186.6 1034.34   198.3 1032.39   205.21029.001
   209.4 1028.37     2181029.041   242.7 1032.29   270.8 1032.61   287.5 1033.79
   307.7 1037.87   320.8 1043.37     332 1049.28     340 1054.55   343.9 1055.97
   363.3 1065.97   378.9 1073.23   386.5 1077.58     410 1086.97   430.7 1093.11
#Mann= 3 ,-1,0
       0      .1       0   205.2    .045       0     218      .1       0
Bank Sta=205.2,218
XS Rating Curve= 0 ,0
Exp/Cntr(USF)=0,0
Exp/Cntr=0.3,0.1

Type RM Length L Ch R = 1 ,10243   ,249,250.4,249
XS GIS Cut Line= 2
1644692.40163655512994.1071827381644422.39415216513310.223435006
#Sta/Elev= 30
       0 1091.19    27.6 1081.53    60.3 1066.76    90.5 1055.44    96.9 1051.57
   106.8 1042.85   118.4  1034.3   122.7 1031.52   127.1 1029.81   137.1 1028.87
   189.2 1029.31   206.9 1027.95   219.5 1028.35  227.011026.646   230.6 1025.55
   234.8 1025.19   244.8 1026.69   247.9 1027.71   254.9 1032.93   260.4 1035.72
   273.8 1043.92   288.3 1055.32     304  1062.5   316.9 1071.66   332.5 1081.47
   344.2 1087.49   355.8 1092.57     393 1113.07     407 1119.54   415.7  1122.3
#Mann= 3 ,-1,0
       0      .1       0  227.01    .045       0   244.8      .1       0
Bank Sta=227.01,244.8
XS Rating Curve= 0 ,0
Exp/Cntr(USF)=0,0
Exp/Cntr=0.3,0.1

Type RM Length L Ch R = 1 ,9993    ,401.2,403.5,404.3
XS GIS Cut Line= 4
1644517.24052287512802.3337944331644469.58510636512876.271310601
1644429.88210178 512940.238702361644281.84682863513174.189468303
#Sta/Elev= 30
       0 1108.86    15.2 1100.62    28.4 1095.18    42.5 1090.89    58.2 1088.16
    71.1 1083.76   106.8 1062.16   121.1 1056.38     128 1052.63   153.5 1035.61
   166.6 1028.52   175.9 1025.86   204.4 1022.82  213.841018.776  224.351018.781
   232.6  1018.3   236.5 1019.26   245.7 1026.05   266.2 1034.12   280.5 1035.84
   294.7 1038.93   314.2 1039.59   325.8 1042.63   335.2 1047.31   342.3 1052.11
     353 1056.77   368.5 1067.56     384 1080.09     419 1099.12   440.1 1115.33
#Mann= 3 ,-1,0
       0      .1       0  213.84    .045       0  224.35      .1       0
Bank Sta=213.84,224.35
XS Rating Curve= 0 ,0
Exp/Cntr(USF)=0,0
Exp/Cntr=0.3,0.1

Type RM Length L Ch R = 1 ,9589    ,300.6,297.1,294.3
XS GIS Cut Line= 6
 1644287.5538125512564.9964930861644222.18419258512623.186665416
1644165.79585393512672.644571751 1644088.0975185512736.439719751
1644025.26299851512779.063322172 1643951.9465441 512828.57536225
#Sta/Elev= 30
       0 1084.78    20.9 1079.93    44.2 1071.96    77.4 1055.71   130.9 1041.34
   139.8 1038.43   162.3 1028.69   179.7 1017.27     189 1014.46   200.5 1013.19
   205.51011.039     209 1010.63     217 1010.97     226  1010.9   228.7  1011.7
     232 1013.69   238.7 1020.17   242.3 1022.45   251.4 1023.79     280 1030.94
   299.8 1037.04   306.2 1039.96   315.6 1045.64     344 1055.86   355.3  1062.3
   367.1 1072.72   379.4 1082.16   385.8 1084.93   407.8 1092.02   427.5 1103.19
#Mann= 3 ,-1,0
       0      .1       0   205.5    .045       0     217      .1       0
Bank Sta=205.5,217
XS Rating Curve= 0 ,0
Exp/Cntr(USF)=0,0
Exp/Cntr=0.3,0.1

Type RM Length L Ch R = 1 ,9292    ,303.1,305.9,306.8
XS GIS Cut Line= 6
1643994.88477843 512319.416603671643954.96130183512397.775042757
1643923.18577483512466.1361265031643890.65926509512560.772420168
1643866.35780451512631.7552178351643832.48976201512712.549019501
#Sta/Elev= 30
       0 1074.59    29.8 1060.37    51.9 1051.57    70.3 1046.19    99.6 1040.26
   124.9 1034.47   157.5 1024.37   161.8  1022.1     172 1014.62   185.4 1006.97
   188.9 1006.47   202.8 1007.19   206.3 1006.51   213.2 1005.94   217.91006.562
   223.6 1008.71   226.3 1009.08   251.4 1009.12   267.6 1010.67   274.4 1012.42
   288.2 1019.57   314.9 1031.69   335.1  1044.2   341.6 1047.84   359.4 1055.69
   372.4 1064.77   398.5  1081.1   402.5  1082.8   407.5 1084.12     426 1086.99
#Mann= 3 ,-1,0
       0      .1       0   206.3    .045       0   217.9      .1       0
Bank Sta=206.3,217.9
XS Rating Curve= 0 ,0
Exp/Cntr(USF)=0,0
Exp/Cntr=0.3,0.1

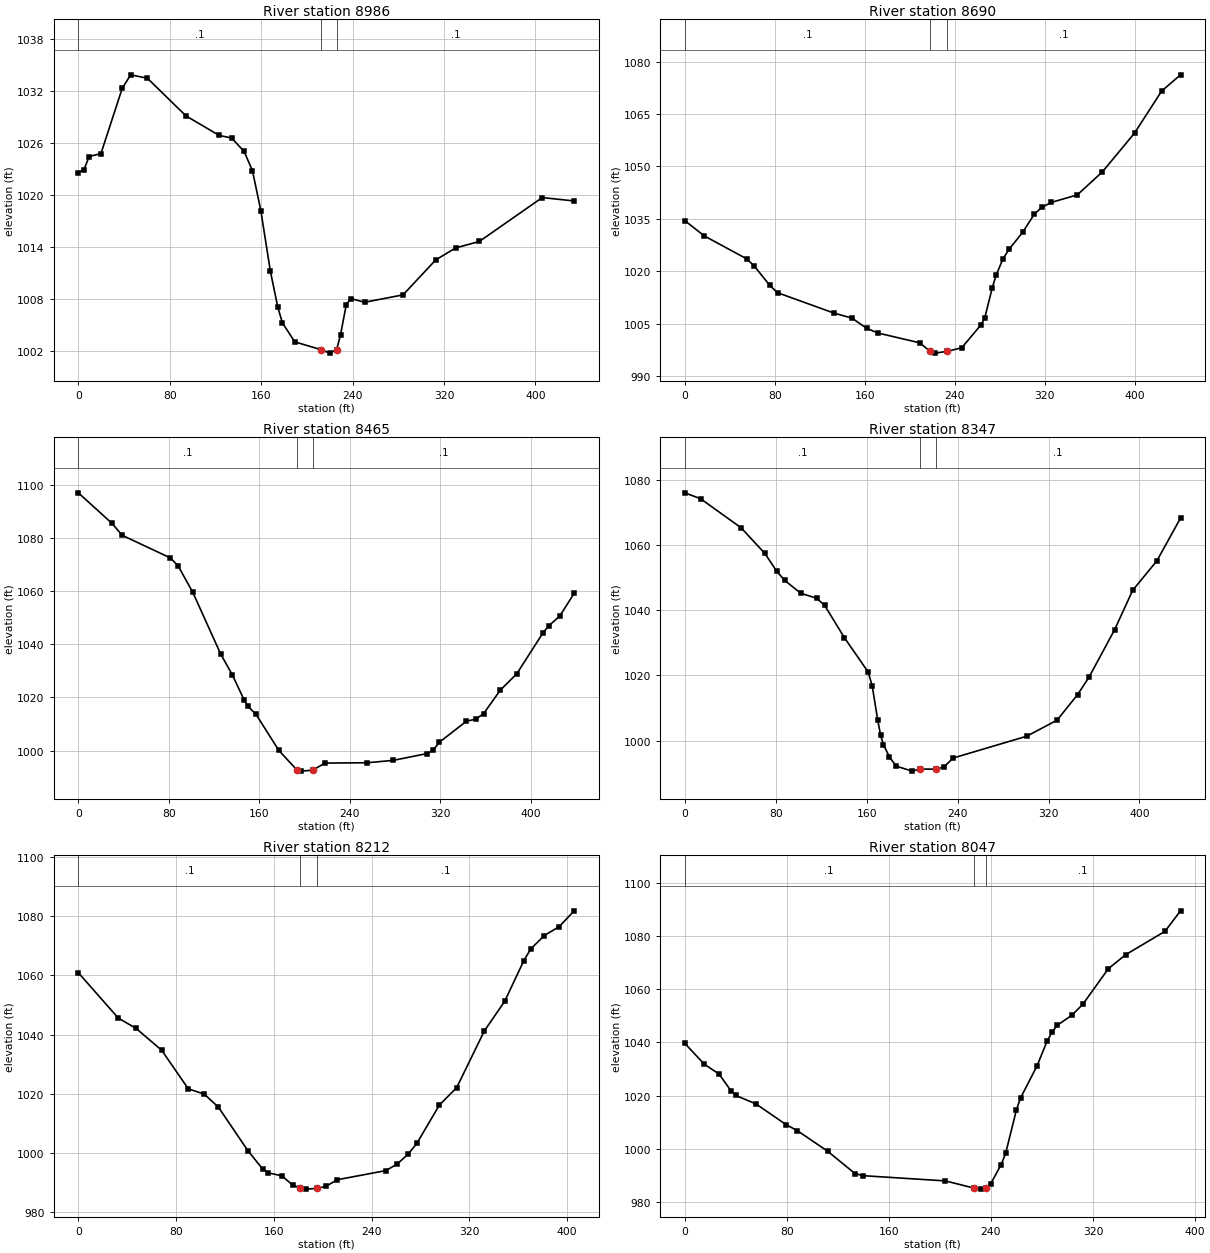
Type RM Length L Ch R = 1 ,8986    ,288,296.4,305.8
XS GIS Cut Line= 6
1643748.00042967512187.4880617561643704.23312876512269.154237002
1643670.45727767512339.4736501721643613.01710384512422.278274596
1643565.54213317512480.300468251  1643510.155761512547.988653094
#Sta/Elev= 30
       0 1022.59     4.9 1022.92     9.5 1024.44    19.8 1024.78    38.4 1032.29
    45.8 1033.85    60.4 1033.46    94.3 1029.11   123.3 1026.87   134.2 1026.57
   145.1 1025.02   152.4  1022.8   159.7 1018.22   168.1 1011.21   174.6 1007.06
   178.6 1005.28   189.4 1003.09   212.1  1002.2     220 1001.79   226.11002.199
   229.5 1003.92   234.5 1007.38   238.5 1008.08   250.5 1007.65   284.2  1008.5
   312.7 1012.52   330.2 1013.91   350.9 1014.65     406 1019.71   433.9 1019.32
#Mann= 3 ,-1,0
       0      .1       0   212.1    .045       0   226.1      .1       0
Bank Sta=212.1,226.1
XS Rating Curve= 0 ,0
Exp/Cntr(USF)=0,0
Exp/Cntr=0.3,0.1

Type RM Length L Ch R = 1 ,8690    ,230.2,224.8,217.7
XS GIS Cut Line= 6
1643700.17309751512134.1052945111643608.57912059512162.389030591
1643530.69377768 512165.695126341643433.78452267512141.015385672
1643361.23742367512121.9904893341643270.06536192512131.390404925
#Sta/Elev= 30
       0 1034.48    17.2 1030.11      55 1023.52    61.9 1021.41    75.6 1015.89
    82.5 1013.82   132.3 1008.02   148.7 1006.54   161.5 1003.64   171.7 1002.28
   208.9  999.47     218997.0329   222.4  996.53   232.9997.0329   246.1  998.06
   263.1 1004.58   266.5 1006.55   273.2  1015.2   276.6 1018.81   282.8 1023.55
   288.2 1026.26   300.4  1031.2   310.5 1036.27   317.3 1038.29   325.8 1039.68
   348.8 1041.83     371  1048.4   399.6  1059.5   423.7 1071.54   440.5 1076.19
#Mann= 3 ,-1,0
       0      .1       0     218    .045       0   232.9      .1       0
Bank Sta=218,232.9
XS Rating Curve= 0 ,0
Exp/Cntr(USF)=0,0
Exp/Cntr=0.3,0.1

Type RM Length L Ch R = 1 ,8465    ,122.8,118.6,114.6
XS GIS Cut Line= 3
 1643526.2712162511762.8845496331643480.37900326 511912.96448925
1643252.15826863512077.928389822
#Sta/Elev= 30
       0 1097.08    29.9 1085.53    38.7  1081.1    81.4 1072.56    88.3 1069.52
   101.2 1059.63     126 1036.26   136.3 1028.45   146.6 1019.08     150 1016.64
   157.1 1013.67   177.3 1000.06   193.5   992.6   196.9  992.24   207.3  992.59
   218.1  995.27   255.7   995.4   278.5  996.29   308.1  998.83   313.7 1000.03
   319.3 1003.12   343.3 1011.05   351.4 1011.81   358.5 1013.92   373.1 1022.69
   387.8 1028.93   410.7 1044.15   416.1 1047.02   425.7 1050.59   438.5 1059.18
#Mann= 3 ,-1,0
       0      .1       0   193.5    .045       0   207.3      .1       0
Bank Sta=193.5,207.3
XS Rating Curve= 0 ,0
Exp/Cntr(USF)=0,0
Exp/Cntr=0.3,0.1

Type RM Length L Ch R = 1 ,8347    ,131.5,135.3,137.4
XS GIS Cut Line= 6
1643415.48302496511682.6885448951643385.26392531511764.805834736
1643359.36174614511835.1925049831643324.82605406511929.039758231
1643286.25493697 511994.87952156 1643212.7288373512058.532281395
#Sta/Elev= 30
       0 1076.04    13.9 1074.24    49.5 1065.33    70.5 1057.44      81 1051.92
      88 1049.15     102 1045.24     116 1043.69     123 1041.53   140.4 1031.61
   161.4 1021.03   164.9 1016.76   169.7  1006.4   172.3  1001.6   174.8  998.79
     180  995.03   185.9  992.21   199.9  990.66   206.9  991.31   220.8  991.25
   227.8   991.9   236.2  994.69   300.8 1001.37   327.5  1006.3   345.5 1014.11
   355.6 1019.48   378.1 1034.04     394 1046.13   415.3 1055.19   436.1  1068.3
#Mann= 3 ,-1,0
       0      .1       0   206.9    .045       0   220.8      .1       0
Bank Sta=206.9,220.8
XS Rating Curve= 0 ,0
Exp/Cntr(USF)=0,0
Exp/Cntr=0.3,0.1

Type RM Length L Ch R = 1 ,8212    ,163.8,164.4,164.3
XS GIS Cut Line= 2
1643369.65907218511669.8099450171643084.69746826511958.537561322
#Sta/Elev= 30
       0 1060.89    32.7 1045.58    47.3 1042.07    68.2 1034.72      90 1021.68
     103 1019.92   114.6 1015.52   138.7 1000.84   150.8  994.63   155.4  993.33
   166.4  992.33   175.6  989.16   181.7988.1418   186.5  987.83   195.2988.0718
   202.7  988.81     212  991.01   251.4  994.06   260.7  996.22     270  999.69
     277 1003.28   295.5 1016.24   309.6  1022.1   332.3 1041.28   348.9 1051.24
   364.6    1065   370.3 1068.95   381.3 1073.43   393.6 1076.48   405.7 1081.78
#Mann= 3 ,-1,0
       0      .1       0   181.7    .045       0   195.2      .1       0
Bank Sta=181.7,195.2
XS Rating Curve= 0 ,0
Exp/Cntr(USF)=0,0
Exp/Cntr=0.3,0.1

Type RM Length L Ch R = 1 ,8047    ,127.7,129.5,129.5
XS GIS Cut Line= 2
1643286.80679967511595.7450347481642967.95108427511817.939765556
#Sta/Elev= 30
       0 1039.65    15.3 1031.79    26.8 1028.12    36.1 1021.89    40.1 1020.02
    55.9 1016.83    79.4 1009.07    88.1 1006.85   112.1  999.02   133.6   990.6
   140.1  989.86   204.3   987.9  226.33985.2404     232  984.81     236  985.24
   239.7  986.75     248  994.02   251.5  998.24     260 1014.68   263.2 1019.09
     276 1031.04     284 1040.44     288 1043.91     292 1046.44   303.3 1050.15
     312 1054.31     332 1067.69   345.7    1073   376.4 1081.74   388.6 1089.46
#Mann= 3 ,-1,0
       0      .1       0  226.33    .045       0     236      .1       0
Bank Sta=226.33,236
XS Rating Curve= 0 ,0
Exp/Cntr(USF)=0,0
Exp/Cntr=0.3,0.1

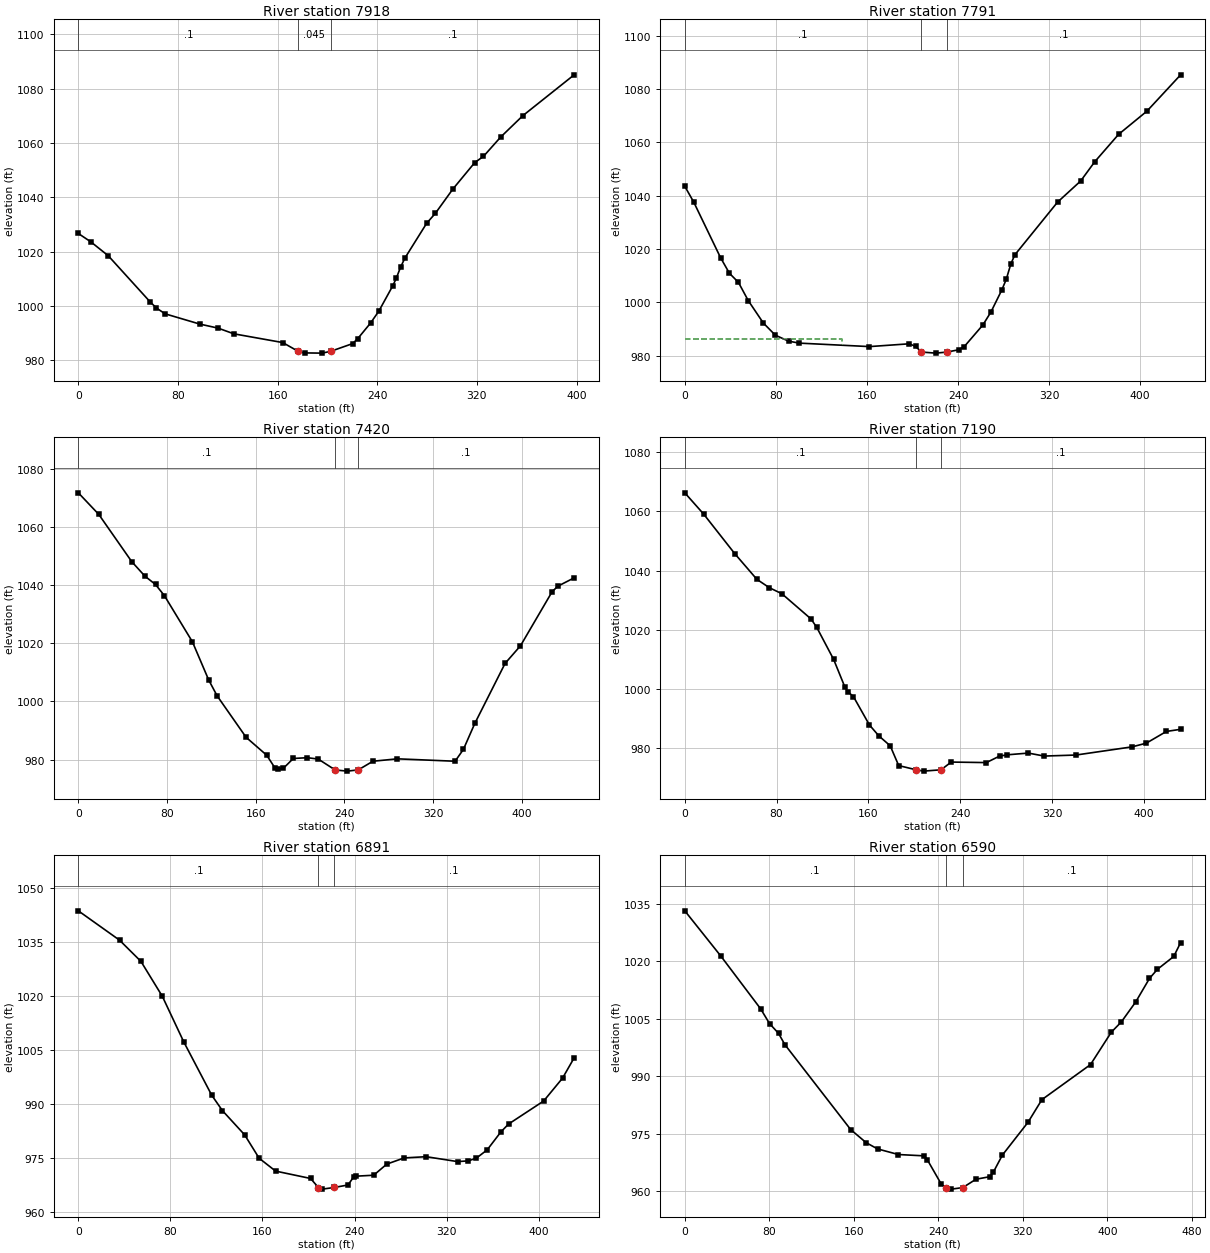
Type RM Length L Ch R = 1 ,7918    ,132.6,126.9,118.8
XS GIS Cut Line= 2
1643233.77164518511541.7153861511642860.92504502511681.136777712
#Sta/Elev= 30
       0 1026.68      10 1023.62      24  1018.5    57.5 1001.59    62.6   999.3
    69.6  997.13    97.6  993.34   112.2  991.86   124.9  989.76   164.1  986.55
  176.53983.3215   181.7  982.74   195.7  982.66  202.58983.3152   220.2  986.16
   224.4  988.03   234.6  993.71   241.2  998.06   252.4 1007.38   255.2 1010.12
   258.7 1014.26   262.2 1017.63   279.7 1030.46   286.7 1034.12   300.7 1043.02
   318.3 1052.78   325.3 1055.06   339.1 1062.16   356.9 1070.03   398.1 1085.06
#Mann= 3 ,-1,0
       0      .1       0  176.53    .045       0  202.58      .1       0
Bank Sta=176.53,202.58
XS Rating Curve= 0 ,0
Exp/Cntr(USF)=0,0
Exp/Cntr=0.3,0.1

Type RM Length L Ch R = 1 ,7791    ,353.7,371,375.8
XS GIS Cut Line= 6
1643148.97833376511373.2295196651643070.69732234511424.292081594
1643009.61115843511474.8201957491642948.88719851511554.273448929
1642903.62908693 511614.078775511642844.42776176 511678.86506325
#Sta/Elev= 30
       0 1043.57     7.9  1037.6    31.4 1016.81    39.2 1010.95    47.1 1007.55
    55.7 1000.73      69  992.29    79.5  987.74    91.3  985.48   100.7  984.76
   162.2  983.46   197.2  984.51   202.7  983.52   207.9981.4152   220.4  981.01
   230.2981.3986   240.8  982.29   245.5  983.48   261.8  991.56   268.9  996.44
   278.3 1004.57   282.3 1008.62   286.4 1014.49   289.9 1017.87   327.4 1037.63
   347.7 1045.56   360.1 1052.79     381 1063.04   405.9 1071.75   435.5 1085.37
#Mann= 3 ,-1,0
       0      .1       0   207.9    .045       0   230.2      .1       0
#XS Ineff= 2 , 0
          138.12  986.15
Permanent Ineff=
       F       F
Bank Sta=207.9,230.2
XS Rating Curve= 0 ,0
Exp/Cntr(USF)=0,0
Exp/Cntr=0.3,0.1

Type RM Length L Ch R = 1 ,7420    ,240.8,229.2,217.5
XS GIS Cut Line= 5
1643046.52479851511150.491448089  1642964.837954511200.725599587
1642870.43933151511251.1590260621642789.14265305511253.356233588
1642736.57277609511407.611341822
#Sta/Elev= 30
       0 1071.77    18.4 1064.37    48.1 1048.14      60 1043.13    69.6 1040.24
    77.6 1036.42   102.9 1020.52   117.6 1007.38   125.2 1001.93   151.3  987.69
   169.9  981.52   177.3  977.16     180  976.66   184.8  976.98   193.9   980.4
   206.6  980.67   216.4  980.19   231.7976.4419   242.7  976.05   252.5  976.48
   265.7  979.45   287.8  980.28   339.8  979.45   347.3  983.52   357.6  992.46
   384.9  1013.1   398.8 1019.17   427.4 1037.81   432.6 1039.68   447.2 1042.53
#Mann= 3 ,-1,0
       0      .1       0   231.7    .045       0   252.5      .1       0
Bank Sta=231.7,252.5
XS Rating Curve= 0 ,0
Exp/Cntr(USF)=0,0
Exp/Cntr=0.3,0.1

Type RM Length L Ch R = 1 ,7190    ,296.5,299.8,302.5
XS GIS Cut Line= 6
1642818.85366592510888.3387571721642781.28681192510967.364189669
1642749.08707318511035.0999465881642706.15244776511125.414070427
1642665.56952368511189.0412397531642594.99748634511251.384947091
#Sta/Elev= 30
       0 1066.32    16.5 1059.09    43.5 1045.74    62.8 1037.03    73.7 1034.19
    84.6 1032.15     110 1023.61     115 1020.75   129.7 1009.92   139.6 1000.46
     142  999.03     147  997.29   160.9  987.71   169.1  984.02     179  980.66
   186.4  973.96   201.5972.5396   208.1  972.08   223.3  972.53   232.2  975.15
   262.8  974.97   274.3  977.17   281.1  977.61   299.4  978.19   313.2  977.18
   340.9  977.53   389.8   980.3   402.2  981.55   419.7  985.52   432.1  986.24
#Mann= 3 ,-1,0
       0      .1       0   201.5    .045       0   223.3      .1       0
Bank Sta=201.5,223.3
XS Rating Curve= 0 ,0
Exp/Cntr(USF)=0,0
Exp/Cntr=0.3,0.1

Type RM Length L Ch R = 1 ,6891    ,301.9,300.2,290.2
XS GIS Cut Line= 6
   1642652.62598510740.8436453341642590.69434534510802.772655338
1642538.08158967510856.2869840121642470.28087226510929.793070585
1642418.06608167510983.6722279191642362.14788643511058.194060504
#Sta/Elev= 30
       0 1043.79    35.8 1035.64    54.4 1029.74      73 1020.03    91.6 1007.38
   115.9  992.56   125.2  988.28   144.5  981.55   157.1  975.05   171.4  971.48
   201.8  969.43   208.6966.9031     212  966.47   222.2966.9239   234.3  967.62
   239.1  969.81   241.3  970.07   256.6  970.33     268  973.42   283.1  975.14
   302.2  975.48   329.5  974.12   338.8  974.32   345.8  975.07   355.2  977.37
   367.3  982.43   373.9  984.57   404.3  990.95   420.7   997.3   430.8 1002.95
#Mann= 3 ,-1,0
       0      .1       0   208.6    .045       0   222.2      .1       0
Bank Sta=208.6,222.2
XS Rating Curve= 0 ,0
Exp/Cntr(USF)=0,0
Exp/Cntr=0.3,0.1

Type RM Length L Ch R = 1 ,6590    ,284.5,300,310.6
XS GIS Cut Line= 6
1642350.25913067510616.9583944231642277.82915743510706.450997591
1642235.43685375510787.6965700091642239.13763376510887.628128678
1642241.91321875510962.5767976791642245.15140125511050.016911507
#Sta/Elev= 30
       0 1033.18    34.2 1021.34    71.8 1007.59    80.2 1003.75    88.7  1001.2
    94.7  998.26     157  976.08   171.6  972.67   182.4  971.03   202.2  969.56
   226.4  969.22   229.7  968.12   242.8  961.82  246.76960.9321   252.4  960.53
   263.1  960.93   275.6  963.11   288.7  963.78     292  964.94   300.6  969.42
   324.9     978     338  983.89     384  993.04   403.7  1001.5   413.2 1004.18
   426.8  1009.4   439.8 1015.52   447.2 1017.88   462.8 1021.27   469.3 1024.89
#Mann= 3 ,-1,0
       0      .1       0  246.76    .045       0   263.1      .1       0
Bank Sta=246.76,263.1
XS Rating Curve= 0 ,0
Exp/Cntr(USF)=0,0
Exp/Cntr=0.3,0.1

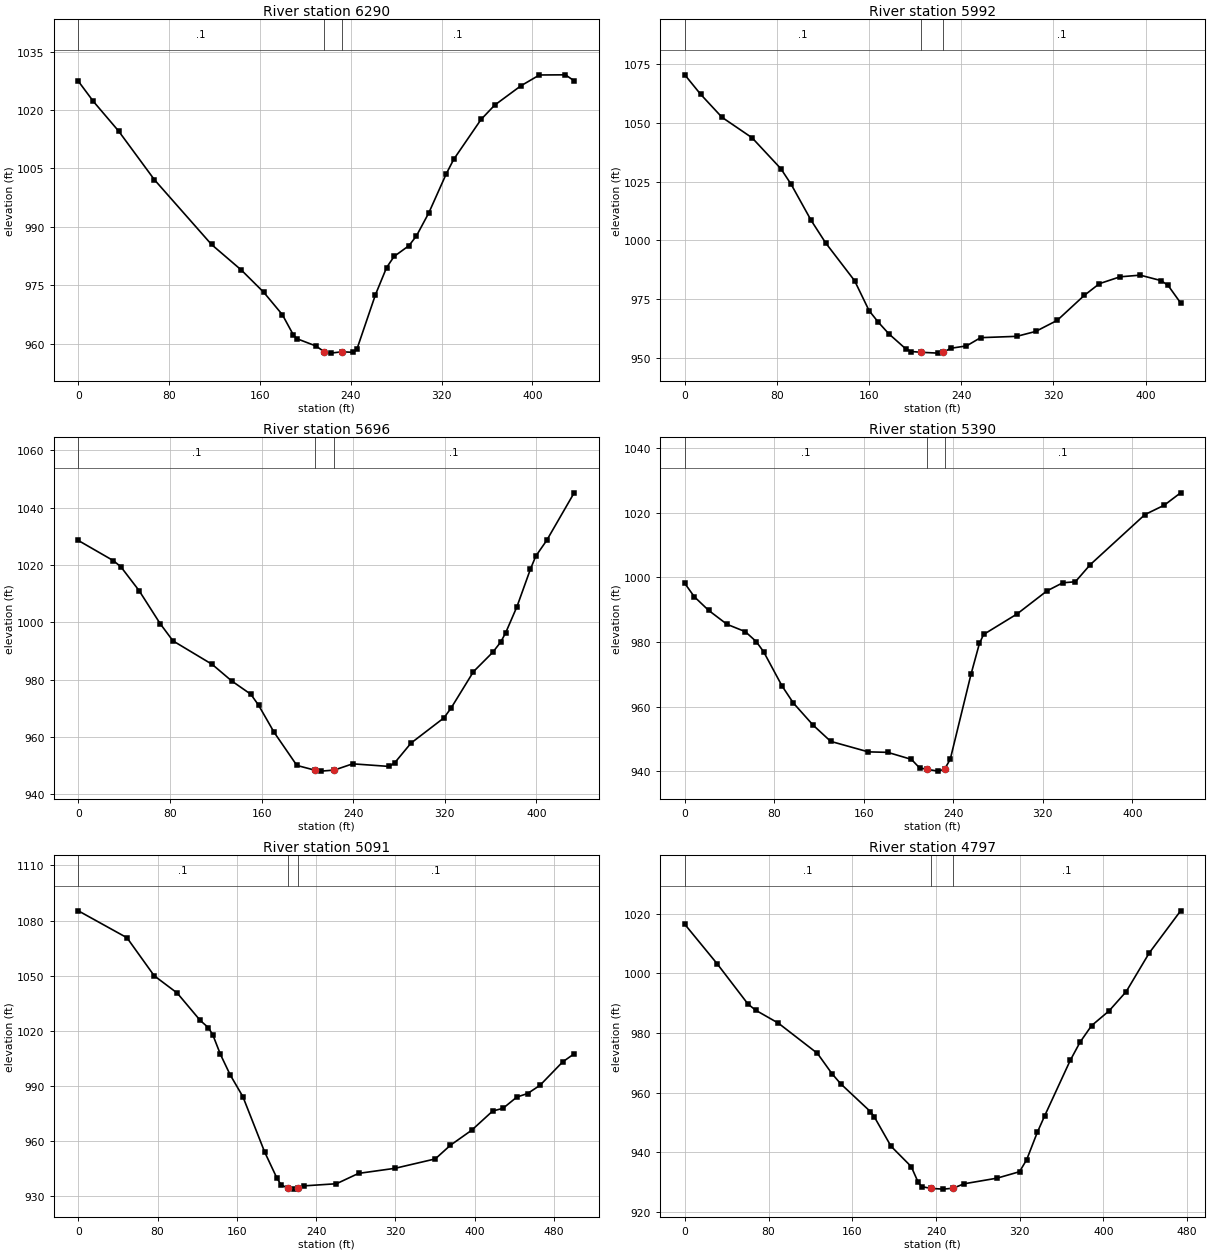
Type RM Length L Ch R = 1 ,6290    ,302.2,298.8,293.8
XS GIS Cut Line= 6
1642333.95535751510571.6917526721642245.22193918 510615.91738601
1642170.22208917 510615.91738601 1642070.2219611 510615.91738601
1641995.22178301 510615.917386011641907.67733867510615.191337585
#Sta/Elev= 30
       0 1027.39    13.2 1022.22    35.4 1014.62      67  1002.1   117.3  985.47
   143.6   978.9   163.3   973.2   179.7  967.45   189.5   962.2   192.8  961.25
   209.2  959.42   216.5957.9557   222.3  957.58   232.2  957.92     242  957.79
   245.3  958.54   261.7  972.59   271.5  979.55   278.1   982.4   291.2  985.17
   297.8  987.68   308.7   993.6     324 1003.58   330.6 1007.32   354.7 1017.57
   366.7 1021.25   389.7 1026.19   406.1 1028.99     429 1029.03   436.7 1027.49
#Mann= 3 ,-1,0
       0      .1       0   216.5    .045       0   232.2      .1       0
Bank Sta=216.5,232.2
XS Rating Curve= 0 ,0
Exp/Cntr(USF)=0,0
Exp/Cntr=0.3,0.1

Type RM Length L Ch R = 1 ,5992    ,293.8,295.3,296.3
XS GIS Cut Line= 6
1642216.27613093510222.6701410111642151.61910801510283.449547008
1642091.96568401 510330.726027251642002.90615085510377.344700426
1641942.16709909510422.8544519251641876.72825359510483.350393921
#Sta/Elev= 30
       0  1070.4    13.7 1062.15    32.3 1052.33    58.4 1043.63    83.4 1030.48
    92.3 1023.85   109.7 1008.47   122.3   998.9   147.4  982.84     160   970.1
   167.9  965.24   177.1  960.27   191.8  953.87   196.7  952.73     205  952.41
   219.8  952.05   224.3952.4174   230.9  954.12   244.5  955.11   256.8  958.63
   288.2  959.19   304.6  961.28   323.3  965.99   346.7  976.58   359.9  981.59
   377.8   984.5   395.3  985.21   413.5  982.88   419.5  980.85   430.4  973.39
#Mann= 3 ,-1,0
       0      .1       0     205    .045       0   224.3      .1       0
Bank Sta=205,224.3
XS Rating Curve= 0 ,0
Exp/Cntr(USF)=0,0
Exp/Cntr=0.3,0.1

Type RM Length L Ch R = 1 ,5696    ,298.5,305.9,310.8
XS GIS Cut Line= 6
1642050.76957217510075.5788997561641971.88718401510117.173960924
  1641898.844023510134.2539792511641802.65983218510163.394340917
1641737.04579018 510205.023522751641663.04200117510257.132670507
#Sta/Elev= 30
       0 1028.54    30.7 1021.47    37.2 1019.32      53 1011.06    71.5  999.47
    82.6   993.5   116.9  985.27   133.8  979.53   150.6  974.85   157.4  971.01
   170.9  961.58   190.8     950   206.2948.3757   212.1  948.01   223.5948.3771
   239.5  950.56   271.6  949.64   276.4     951   290.5  957.81   319.2   966.6
   325.5  970.06     345  982.75   361.8  989.49   368.8  993.09   373.1  996.31
     383 1005.48   394.7 1018.52   399.4 1023.07   408.9 1028.56   432.9 1045.18
#Mann= 3 ,-1,0
       0      .1       0   206.2    .045       0   223.5      .1       0
Bank Sta=206.2,223.5
XS Rating Curve= 0 ,0
Exp/Cntr(USF)=0,0
Exp/Cntr=0.3,0.1

Type RM Length L Ch R = 1 ,5390    ,302.4,299.3,286.5
XS GIS Cut Line= 6
1641989.12369809509948.1638002541641892.07894467509947.195626333
1641816.35501476509930.3347676691641728.30827484509882.924101338
1641662.27363001 509847.365445421641569.33746417509836.284430832
#Sta/Elev= 30
       0  998.16     8.5  994.03    21.3  989.81    37.7   985.5    54.1  983.22
    63.9  980.14    70.5  976.98    86.9  966.43      97  961.16   114.6  954.33
   130.4  949.28     164  946.03   181.4  945.88   202.6   943.7   209.8  941.08
   216.5940.6514   226.2  940.07   232.2  940.65   237.3  943.77   255.8     970
   263.4  979.63   267.1  982.36     297   988.7   323.7  995.83   337.9  998.35
   349.1  998.66   362.4 1003.95   411.3 1019.45   428.5 1022.34   443.2 1026.18
#Mann= 3 ,-1,0
       0      .1       0   216.5    .045       0   232.2      .1       0
Bank Sta=216.5,232.2
XS Rating Curve= 0 ,0
Exp/Cntr(USF)=0,0
Exp/Cntr=0.3,0.1

Type RM Length L Ch R = 1 ,5091    ,297.2,293.9,288.1
XS GIS Cut Line= 6
1641966.45379592509477.4655946791641909.29577376509543.717430666
1641860.30308959509600.504718676 1641785.0571771 509690.11280717
1641695.03471933509742.6422296761641585.71768075 509783.92265892
#Sta/Elev= 30
       0 1085.27    49.1 1070.63    76.6 1049.95    99.8 1040.56   123.1 1025.63
   131.4 1021.67   135.8 1017.78   143.5 1007.15   153.3  996.06   166.1  984.23
   188.2  953.98   200.3  940.12   204.5  936.37   211.2934.4721   217.5   933.9
   221.7  934.47   227.8  935.67   260.6  936.83   282.9  942.46   319.8  945.23
   360.4  950.34   375.6  957.74   397.2  965.97   418.3  976.37   428.8  977.86
   442.8  984.01   453.5  985.87   466.1  990.36     489  1003.1   500.6  1007.5
#Mann= 3 ,-1,0
       0      .1       0   211.2    .045       0   221.7      .1       0
Bank Sta=211.2,221.7
XS Rating Curve= 0 ,0
Exp/Cntr(USF)=0,0
Exp/Cntr=0.3,0.1

Type RM Length L Ch R = 1 ,4797    ,282.9,306.8,318.4
XS GIS Cut Line= 6
1641769.07623792509379.5061449261641672.39040767509428.522123009
1641598.32428284509481.7021347581641582.63730635509581.807905674
1641561.13013151509657.7936460821641518.76571493509741.498531178
#Sta/Elev= 30
       0  1016.5      31 1003.21    60.4  989.71    67.7  987.66    89.4  983.31
   126.7  973.17   140.5   966.4   148.8     963   177.3  953.62   180.9  951.94
     197  941.99   216.3  935.16     223  929.85   226.3  928.41   235.2  927.83
   246.7  927.58   256.2  927.87   266.8  929.37   298.4  931.27   319.8  933.43
   326.6  937.45   336.8  946.66   343.7  952.11   368.2  970.78   377.7  976.97
   388.6  982.47   405.3  987.42   421.7   993.9   443.7 1006.88   473.7 1021.03
#Mann= 3 ,-1,0
       0      .1       0   235.2    .045       0   256.2      .1       0
Bank Sta=235.2,256.2
XS Rating Curve= 0 ,0
Exp/Cntr(USF)=0,0
Exp/Cntr=0.3,0.1