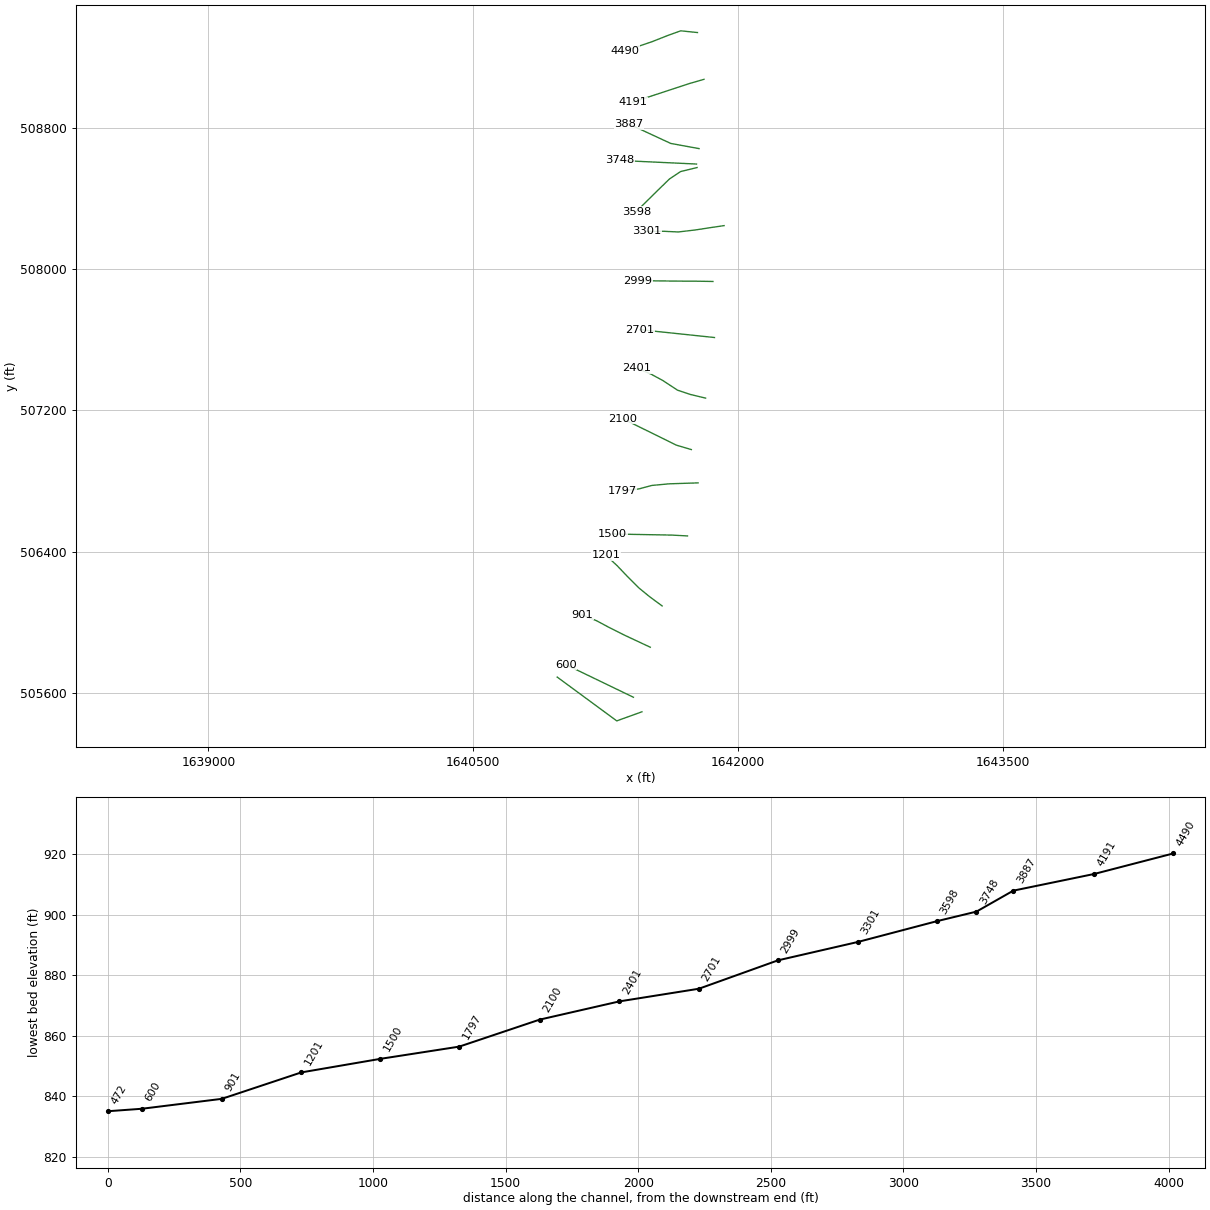
HEC-RAS study NFMidGraveCk.prj: NFMidGraveCk

--- NFMidGraveCk.g01 (geometry) --- (continued)

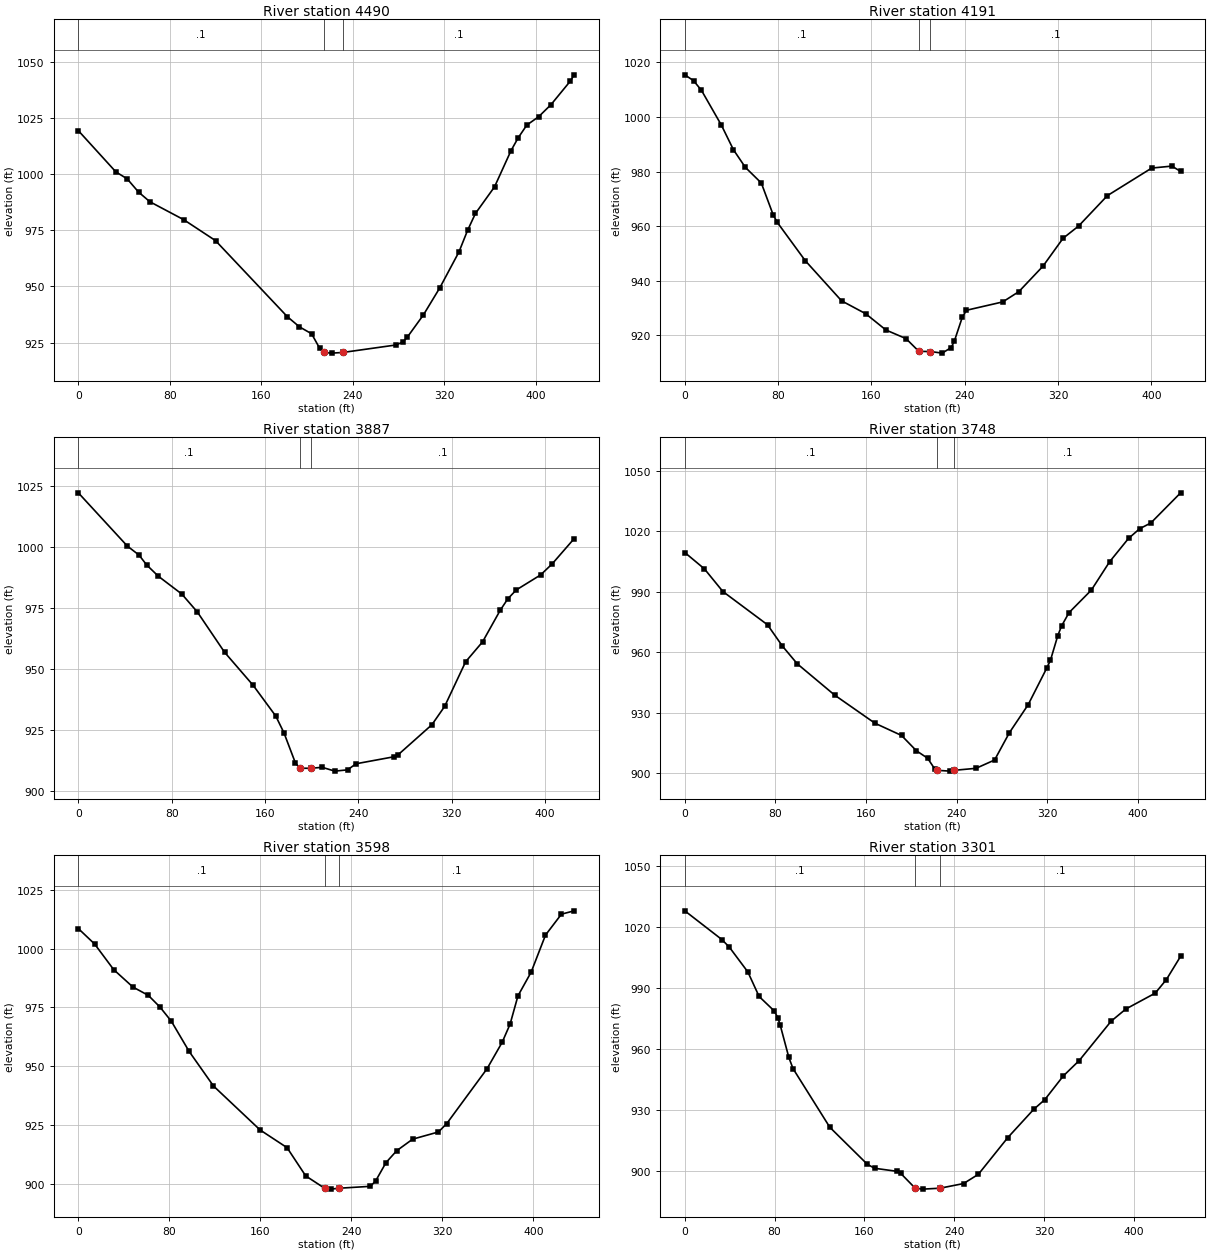
Type RM Length L Ch R = 1 ,4490    ,299.2,299.1,297.1
XS GIS Cut Line= 6
1641770.80031584509340.231289089 1641675.8388916509349.972739428
1641605.22125067509324.6036956761641512.20536059509287.887233675
1641441.04211709509263.9010611771641357.73355667509236.172442093
#Sta/Elev= 30
       0 1019.37    32.8 1001.02    42.7  997.91    52.6  992.04    62.5  987.73
    92.2  979.71   119.9  970.42   182.7  936.56   193.3  932.03   203.9  928.96
     211  922.45   214.5  920.64   221.5  920.34   231.1  920.63   277.8  923.98
   283.5  925.27   287.4  927.34   301.6  937.33   315.9  949.35   332.7  965.38
   340.2  974.93   347.1   982.5   363.8  994.35   378.2 1010.47   384.5  1016.2
     392 1021.83   402.4 1025.59   413.1 1030.91   430.1 1041.45   433.4 1044.21
#Mann= 3 ,-1,0
       0      .1       0   214.5    .045       0   231.1      .1       0
Bank Sta=214.5,231.1
XS Rating Curve= 0 ,0
Exp/Cntr(USF)=0,0
Exp/Cntr=0.3,0.1

Type RM Length L Ch R = 1 ,4191    ,307.7,304.9,300.8
XS GIS Cut Line= 6
1641807.73298475509075.2075409291641723.63899285509050.835214332
1641652.38651067509027.4241719251641557.38309176508996.209011257
1641486.13028151508972.7982969281641403.00216693508945.486015588
#Sta/Elev= 30
       0 1015.46     7.5 1013.32    14.3 1009.77    31.4  997.01    41.7  988.02
    51.9  981.58    65.6  975.84    75.8  964.15    79.2  961.47   103.3  947.38
   134.4  932.69   155.1  927.96   172.4  922.01   189.7  918.84   200.7914.1605
   210.4  914.12   220.7  913.53   228.4  915.58   231.1  917.93     238  926.79
   241.5  929.23   272.6  932.29   286.4  936.05   307.1  945.38   324.3  955.59
   337.6  960.07   362.3  971.21   400.3  981.31   417.6  982.03   425.1  980.08
#Mann= 3 ,-1,0
       0      .1       0   200.7    .045       0   210.4      .1       0
Bank Sta=200.7,210.4
XS Rating Curve= 0 ,0
Exp/Cntr(USF)=0,0
Exp/Cntr=0.3,0.1

Type RM Length L Ch R = 1 ,3887    ,134.3,139,140.2
XS GIS Cut Line= 3
1641779.46848013508682.766753588 1641619.2056202508712.019884351
1641381.56154723508822.295017259
#Sta/Elev= 30
       0 1022.13      42  1000.3      52  996.61    58.6  992.54    68.6  987.92
    88.7  980.61     102  973.26   125.3  956.77   149.9  943.14   169.2  930.59
   176.2  923.73   186.1  911.26  190.06909.1897   199.1  909.18     209  909.57
   219.8  908.01   230.7  908.53     238  911.03   270.5   913.9   274.1  914.74
     303  927.04   313.9  934.54   331.9  952.86   346.4  961.01   361.5  973.94
   368.1   978.7   375.3  982.31   396.1  988.45     406  992.96   424.9 1003.35
#Mann= 3 ,-1,0
       0      .1       0  190.06    .045       0   199.1      .1       0
Bank Sta=190.06,199.1
XS Rating Curve= 0 ,0
Exp/Cntr(USF)=0,0
Exp/Cntr=0.3,0.1

Type RM Length L Ch R = 1 ,3748    ,143.2,149.8,154.6
XS GIS Cut Line= 2
1641765.22046853508595.2686813551641328.07738794508615.600917661
#Sta/Elev= 30
       0 1009.47    17.3 1001.36    33.6  990.13      73  973.63    86.2  963.03
    99.3  954.26   132.2  938.79   167.8  924.83   191.3  918.75   204.4  911.17
   214.3  907.47   220.8  901.97  222.89901.4643     234  901.07   237.7  901.47
     257  902.46   273.4  906.58   286.5  920.14     303  933.97   319.4  952.11
   322.7     956   329.2  968.28   332.5  973.01   339.1  979.66   358.8  990.83
   374.9 1004.86   391.6 1016.44   401.5 1021.28   411.3 1024.11   437.6 1039.06
#Mann= 3 ,-1,0
       0      .1       0  222.89    .045       0   237.7      .1       0
Bank Sta=222.89,237.7
XS Rating Curve= 0 ,0
Exp/Cntr(USF)=0,0
Exp/Cntr=0.3,0.1

Type RM Length L Ch R = 1 ,3598    ,300.9,297.1,289
XS GIS Cut Line= 6
 1641768.4368035508575.4306533341641674.96914268508552.603927344
1641611.97911118508510.5669379231641540.26239109508440.788206086
1641486.39340433508387.6049135031641423.58841184 508325.71100843
#Sta/Elev= 30
       0 1008.51    14.3 1001.96    31.1  991.07      48  983.68    61.5  980.16
    71.7  975.23    81.8  969.15    97.4  956.36   118.8  941.68   159.8  923.01
   183.5  915.49   199.9   903.5   216.5898.2681   221.8  897.89   229.6898.2806
   256.8  899.08   261.4  901.39   270.5  909.16   279.9   914.2   293.9   919.1
   316.6  922.16   323.9  925.73   359.3  948.99   372.6  960.22   379.6  967.98
   386.5  979.95   398.1  990.03   410.7 1005.74   424.7 1014.62   435.9 1016.04
#Mann= 3 ,-1,0
       0      .1       0   216.5    .045       0   229.6      .1       0
Bank Sta=216.5,229.6
XS Rating Curve= 0 ,0
Exp/Cntr(USF)=0,0
Exp/Cntr=0.3,0.1

Type RM Length L Ch R = 1 ,3301    ,301.9,301.6,297.6
XS GIS Cut Line= 6
1641921.76097192508246.4841327521641835.21619751508233.582911834
  1641761.088393508222.178407088 1641661.7322925508210.457630008
 1641579.3193996508214.3628059181641482.66506533508213.371994257
#Sta/Elev= 30
       0 1028.12      33 1013.98    39.7 1010.21    56.2  997.99    66.2  985.93
    79.5   978.9    82.8  975.55    84.9  972.02    92.7  955.87    96.4  950.41
   129.2  921.49   162.5  903.33     169  901.31   188.9  899.81   192.2  898.87
   205.3  891.46     212  891.03   227.3891.4791   248.3  893.77   261.5  898.32
   287.8  916.45   310.8  930.32   320.7  935.11   337.1  946.73   351.4  954.39
   379.8  973.76   392.9  979.75   419.1  987.58     429  994.25   441.7 1005.73
#Mann= 3 ,-1,0
       0      .1       0   205.3    .045       0   227.3      .1       0
Bank Sta=205.3,227.3
XS Rating Curve= 0 ,0
Exp/Cntr(USF)=0,0
Exp/Cntr=0.3,0.1

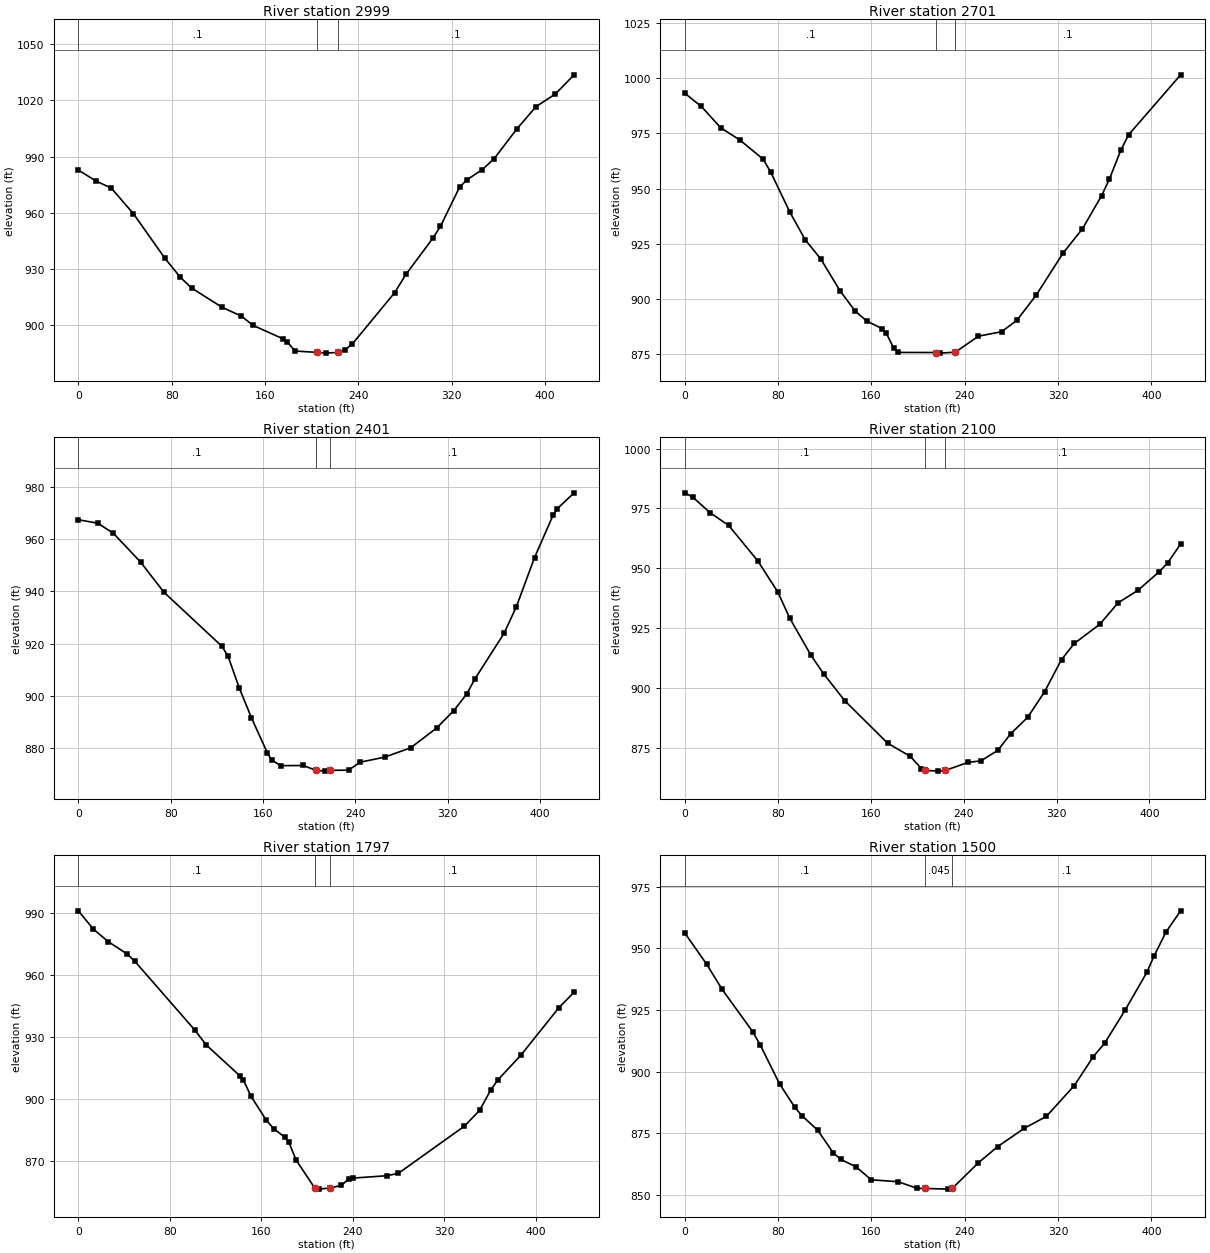
Type RM Length L Ch R = 1 ,2999    ,298.6,298.3,296.9
XS GIS Cut Line= 6
1641858.29882851507930.0103562621641770.76717943507931.487387419
1641695.75617459 507931.821048171641595.75539035507932.707857415
1641520.76407051507933.5385644291641433.27441609507934.511987671
#Sta/Elev= 30
       0  982.79    15.1  976.95    28.3  973.11    47.2  959.48    74.2  935.65
    87.5  925.43    97.2  919.69   123.4  909.37   139.8  904.73   149.7  899.79
   175.9  892.47   179.2  890.96   185.7  886.07     205885.3325     212  884.94
   222.8885.3291   228.4  886.51     235  889.89   271.1  917.17   280.9  927.05
   303.9  946.32   310.4  952.63   326.8  973.59   333.2  977.59   346.2  982.98
   356.4  988.77     376 1004.79   392.4 1016.69   408.9  1023.4   425.1 1033.68
#Mann= 3 ,-1,0
       0      .1       0     205    .045       0   222.8      .1       0
Bank Sta=205,222.8
XS Rating Curve= 0 ,0
Exp/Cntr(USF)=0,0
Exp/Cntr=0.3,0.1

Type RM Length L Ch R = 1 ,2701    ,304.3,299.4,298.5
XS GIS Cut Line= 6
1641867.15182917507612.5024610911641780.13264626507621.662875846
1641705.54454084507629.5125976651641606.09395234507639.979768336
1641531.50584692507647.8304744211641444.48666401507656.989576846
#Sta/Elev= 30
       0  993.09    14.2  987.13    30.7  977.54    47.2  971.93      67  963.36
    73.6  957.49    90.1  939.26   103.3  926.76   116.5  918.18     133  903.77
   146.2  894.46   156.1  890.01   169.3  886.56   172.6  884.63   179.2  877.69
   182.5  875.85   215.5  875.82   218.8  875.54   231.9  875.97   251.7   883.2
   271.5  885.22   284.7  890.42   301.2  901.77   324.3  920.84   340.8  931.74
   357.3  946.81   363.9  954.21   373.8   967.4   380.4  974.31     425 1001.44
#Mann= 3 ,-1,0
       0      .1       0   215.5    .045       0   231.9      .1       0
Bank Sta=215.5,231.9
XS Rating Curve= 0 ,0
Exp/Cntr(USF)=0,0
Exp/Cntr=0.3,0.1

Type RM Length L Ch R = 1 ,2401    ,298.6,301.3,299.4
XS GIS Cut Line= 6
1641816.83926576507269.1435677561641730.06155217507290.042476088
1641657.55940059507314.3705114281641573.46179976507369.527225256
1641507.26016051507405.2079281661641426.32889192507439.657334343
#Sta/Elev= 30
       0  967.33    16.8  966.04    30.3  962.19    53.9  951.19    74.2  939.65
   124.5  918.97   129.7  915.18   139.5     903   149.9  891.77   163.7  878.36
   167.4  875.63   175.3  873.44   194.9  873.51   205.5   871.7   213.3  871.36
   218.4  871.67   234.1  871.72   244.1  874.76   265.4  876.71   287.9  880.27
   310.3  887.79   325.2  894.46   336.3  900.73   343.7  906.69   368.7  923.91
   379.4   934.1   395.2  952.91   411.4  969.24     415  971.63   429.5  977.62
#Mann= 3 ,-1,0
       0      .1       0   205.5    .045       0   218.4      .1       0
Bank Sta=205.5,218.4
XS Rating Curve= 0 ,0
Exp/Cntr(USF)=0,0
Exp/Cntr=0.3,0.1

Type RM Length L Ch R = 1 ,2100    ,298,303,307.7
XS GIS Cut Line= 6
 1641736.0549785 506977.742575751641650.39865376507003.029926762
1641583.21079601507036.359256417 1641493.4927996507080.526162833
1641426.20487642507113.6520808341641347.70175259507152.298000917
#Sta/Elev= 30
       0  981.54     6.9  979.72    21.7  973.26    37.8   967.9    62.8  953.13
    79.9  940.26    90.2  929.32   108.5  913.79   119.5  905.96   137.8  894.66
   174.6  876.97   194.1  871.47   203.7  866.36   206.7865.6434   218.3  865.31
   224.4865.6407   243.9  868.96   254.9   869.6   269.5  873.99   280.5   880.9
   295.1  887.76   309.7  898.45   324.3  911.93   335.3  918.64   357.3  926.68
     373  935.62   390.1  940.83   408.5  948.63   415.8  952.36   426.8  960.21
#Mann= 3 ,-1,0
       0      .1       0   206.7    .045       0   224.4      .1       0
Bank Sta=206.7,224.4
XS Rating Curve= 0 ,0
Exp/Cntr(USF)=0,0
Exp/Cntr=0.3,0.1

Type RM Length L Ch R = 1 ,1797    ,297.2,297,298.2
XS GIS Cut Line= 6
1641774.34197542506789.0077169981641686.88775401506786.186200336
1641611.92661785506783.7675700041641512.15057068506774.492982253
1641437.42827918506754.4470905961641344.20143151506744.293239504
#Sta/Elev= 30
       0     991    13.2  982.12    26.3  976.05    42.7   970.1    49.3  966.67
   101.8  933.39     112  926.07   141.2  911.27   144.5  909.04   151.1  901.29
   164.2  889.94   170.8  885.65   180.7  881.47     184  879.29   190.6   870.4
   206.8856.9534   210.3  856.38   220.6856.9474   230.1   858.2   236.7  861.31
     240  861.71   269.9  862.86     280  864.02   337.8  886.85   351.1   894.5
   360.7   904.2   366.9  909.11   387.4   921.3   420.4  944.12   433.8  951.68
#Mann= 3 ,-1,0
       0      .1       0   206.8    .045       0   220.6      .1       0
Bank Sta=206.8,220.6
XS Rating Curve= 0 ,0
Exp/Cntr(USF)=0,0
Exp/Cntr=0.3,0.1

Type RM Length L Ch R = 1 ,1500    ,306.7,298.8,288.3
XS GIS Cut Line= 6
1641714.25351292506488.3751161691641626.82783476506493.251090676
1641551.84012385 506494.61460501  1641451.856728506496.432186678
1641376.86901709506497.7957010121641289.38362776506499.386577085
#Sta/Elev= 30
       0  956.18    18.8  943.51    31.9  933.41    58.2   916.2    64.8  910.67
    81.2  895.06    94.3  885.53   100.4  882.13     114  876.21   127.1  867.14
   133.7  864.38   146.8   861.4   159.9  856.13   182.9  855.34   199.3  852.65
   205.9  852.62   225.6  852.34   229.3  852.64   251.8  863.05   268.2  869.56
   291.2  877.06   309.9   881.8   333.9   894.3   350.3  906.11   360.1   911.6
   377.6     925   396.2  940.27   402.1  946.67   412.6  956.62   425.1  965.19
#Mann= 3 ,-1,0
       0      .1       0   205.9    .045       0   229.3      .1       0
Bank Sta=205.9,229.3
XS Rating Curve= 0 ,0
Exp/Cntr(USF)=0,0
Exp/Cntr=0.3,0.1

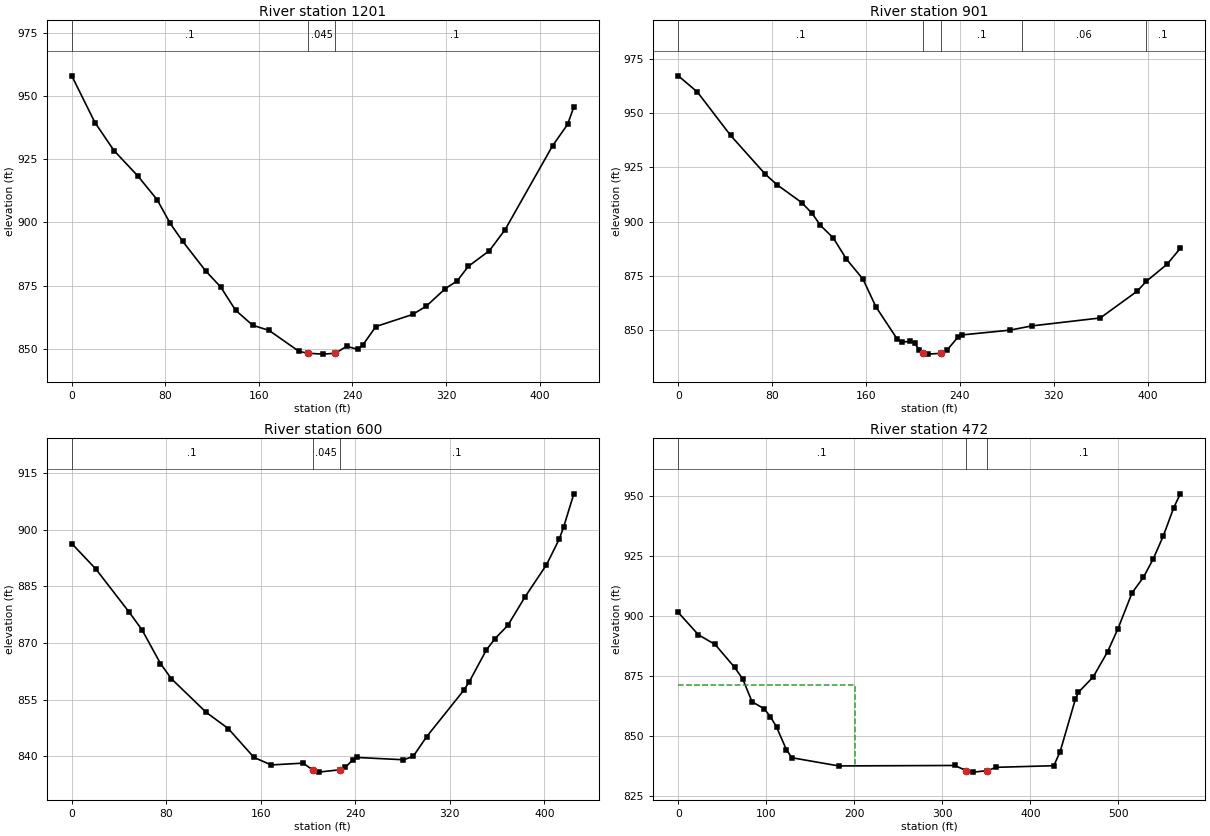
Type RM Length L Ch R = 1 ,1201    ,292.3,299.8,301.3
XS GIS Cut Line= 6
1641570.42243576506091.9828643351641498.28937793506145.182889178
1641438.91974601506193.8537235861641368.08983517506264.869657665
1641316.36520109506319.1795884221641252.44144443506379.117788762
#Sta/Elev= 30
       0  958.06    19.8  939.57    36.1  928.46    56.5  918.39      73     909
    84.2  899.58    94.9  892.48   114.6  880.73   127.3  874.45     140  865.26
   154.7  859.27   168.7  857.23   194.2  848.95   201.7848.1954   215.1  847.84
   225.4 848.194   235.1  850.95   244.4  849.72     249  851.54     260  858.76
   291.4  863.54   303.2  866.86   319.5  873.83   329.5   876.8     339  882.57
   357.1  888.82   370.6  897.19   411.1  930.36   423.9  938.79   429.3  945.72
#Mann= 3 ,-1,0
       0      .1       0   201.7    .045       0   225.4      .1       0
Bank Sta=201.7,225.4
XS Rating Curve= 0 ,0
Exp/Cntr(USF)=0,0
Exp/Cntr=0.3,0.1

Type RM Length L Ch R = 1 ,901     ,302,301.4,300.6
XS GIS Cut Line= 6
1641503.56856684505857.8504585921641424.32167809 505894.94716917
1641356.39563283505926.7443496731641266.80362043505971.770834416
1641200.09115542506007.5319177511641117.54145175506041.930471003
#Sta/Elev= 30
       0  967.19    16.3  959.75    44.6  939.78    74.2  921.91    84.1  917.09
   105.3  908.82   114.1  903.86   121.1  898.41   132.2  892.52   143.3  882.87
   157.5  873.57   168.5  860.84   186.8  845.87   190.5   844.7   197.9  844.91
   201.5  844.09   205.2  841.12   208.7839.4733   212.5  839.09   223.8839.4533
   229.1  840.94   238.3  846.86   241.9  847.93   282.6  850.12   301.2  852.07
   359.7  855.74   391.1  868.04   398.8  872.54   416.6  880.47   427.9  887.77
#Mann= 5 ,-1,0
       0      .1       0   208.7    .045       0   223.8      .1       0
  292.77     .06       0  398.46      .1       0
Bank Sta=208.7,223.8
XS Rating Curve= 0 ,0
Exp/Cntr(USF)=0,0
Exp/Cntr=0.3,0.1

Type RM Length L Ch R = 1 ,600     ,129.7,128.1,125.2
XS GIS Cut Line= 6
1641407.91849567505574.5754345951641329.12042493505612.616040915
1641261.57889333505645.2226030081641171.52395535505688.697581679
1641103.98275185505721.3041437571641024.94124326505758.840814084
#Sta/Elev= 30
       0  896.28    20.4  889.55    48.6  878.13    59.5  873.44    75.1  864.54
    84.2  860.56   113.7  851.65   132.4  847.35   154.2  839.71   168.8  837.71
   195.8  838.19   203.8836.4333   208.9  835.81   227.3836.4419   231.7  837.08
     238  839.12   241.7  839.69   280.8  839.08     289  839.96   300.4  845.19
   331.7  857.42   336.4  859.68   350.9  868.11   358.2  871.12   369.1  874.63
   383.6  882.14   401.8  890.65   412.7  897.52   416.3  900.62     425  909.45
#Mann= 3 ,-1,0
       0      .1       0   203.8    .045       0   227.3      .1       0
Bank Sta=203.8,227.3
XS Rating Curve= 0 ,0
Exp/Cntr(USF)=0,0
Exp/Cntr=0.3,0.1

Type RM Length L Ch R = 1 ,472     ,163,160,154.8
XS GIS Cut Line= 3
 1641456.0728773505492.2175510031641313.51343557505440.654330259
1640976.06659301505688.909813228
#Sta/Elev= 30
       0  901.43      23  892.12    41.9  888.11      64  878.61    73.3  873.76
    83.8  864.32    97.7  861.32   104.7   858.1   111.7  853.77   122.9  844.33
   129.1  840.98   182.4  837.57   314.3  837.76     327835.6234   335.4  834.99
  351.32 835.622   361.2  836.99   426.8  837.66     434  843.57   451.2  865.26
   454.8  868.24   471.6  874.64   487.9  885.13   499.7   894.7   515.7  909.62
   528.6  916.06   539.6   923.6   551.3  933.38     563     945   570.5  950.79
#Mann= 3 ,-1,0
       0      .1       0     327    .045       0  351.32      .1       0
#XS Ineff= 2 , 0
          200.66  871.38
Permanent Ineff=
       F       F
Bank Sta=327,351.32
XS Rating Curve= 0 ,0
Exp/Cntr(USF)=0,0
Exp/Cntr=0.3,0.1