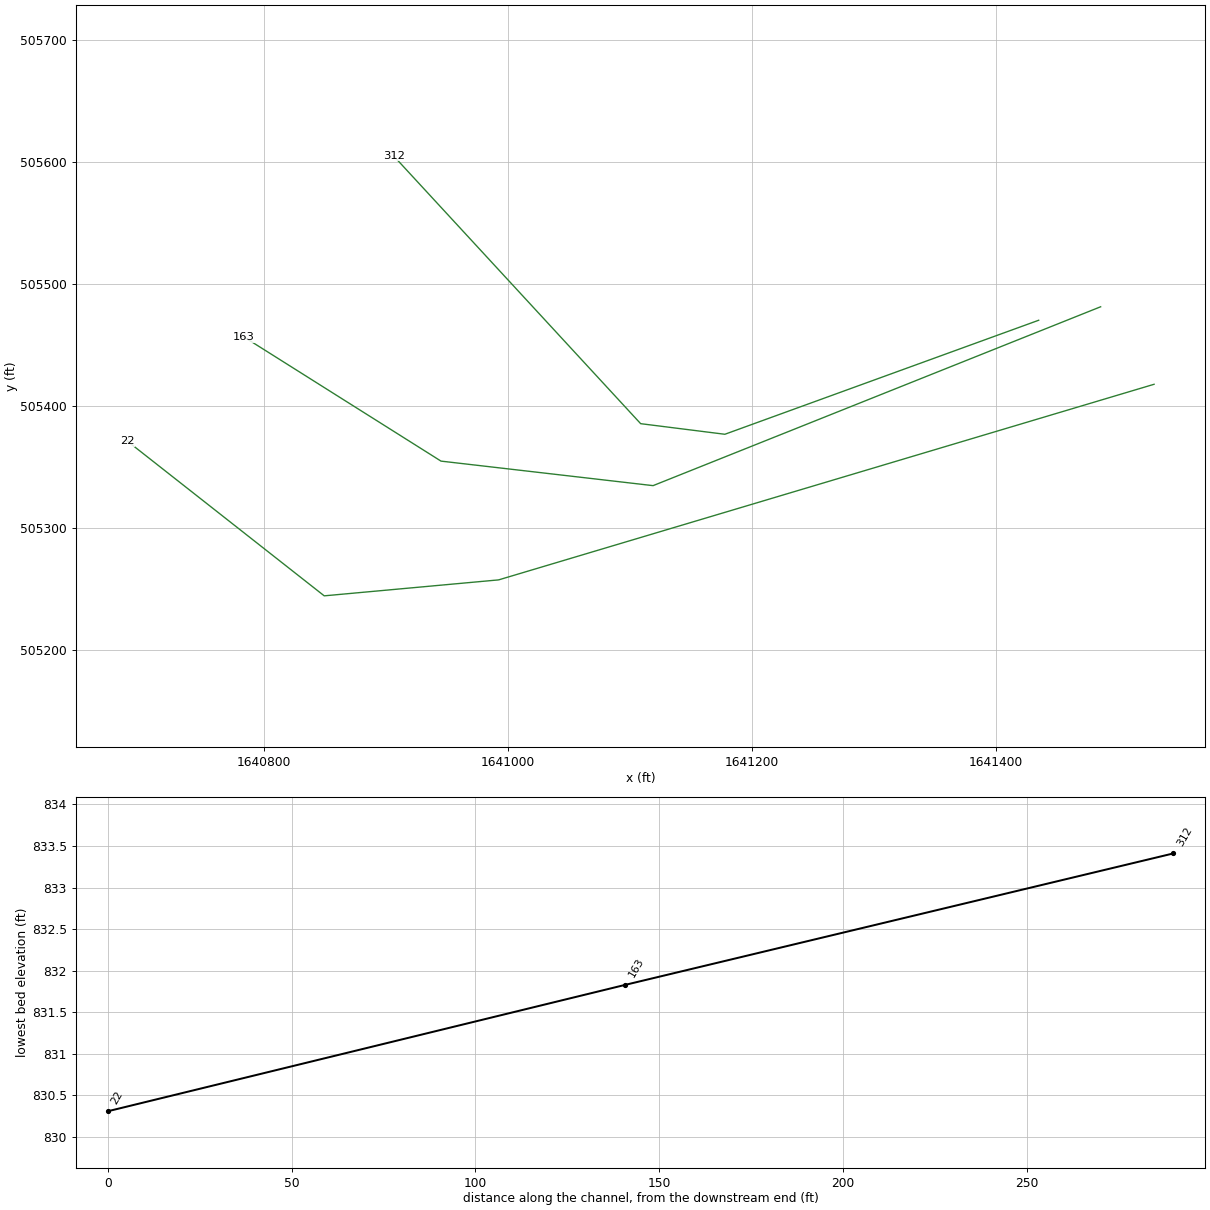
HEC-RAS study NFMidGraveCk.prj: NFMidGraveCk

--- NFMidGraveCk.g01 (geometry) --- (continued)

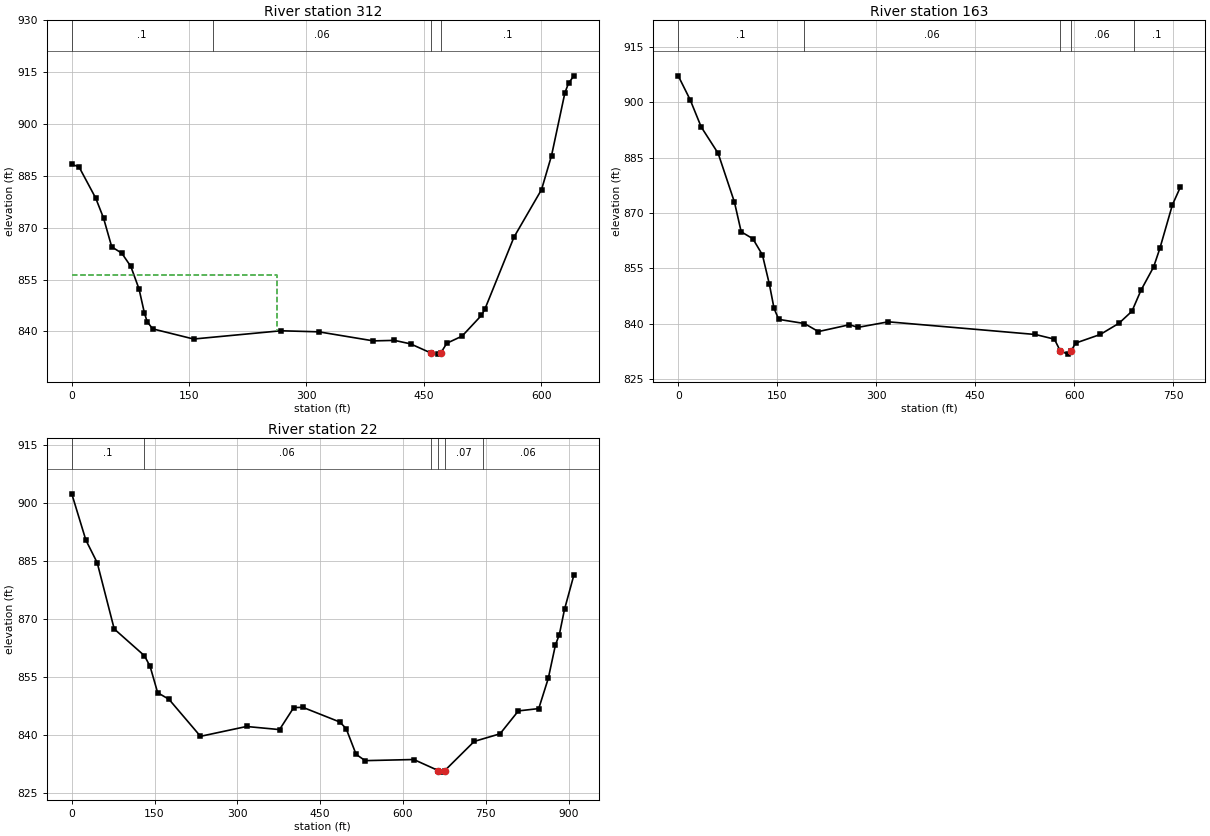
Type RM Length L Ch R = 1 ,312     ,147,149.1,150.8
XS GIS Cut Line= 4
1641435.12428905505470.483121995 1641177.8818599505377.021346839
1641108.86111967505385.7092721831640906.32562289505605.220649081
#Sta/Elev= 30
       0  888.32     9.2  887.61    30.6  878.56    40.6  872.79    51.1  864.44
    63.9  862.63    75.5  858.78      86  852.26    92.9  845.27    96.4  842.81
   103.4  840.72   155.8  837.78   267.5  840.17   315.9  839.86   385.7  837.24
   412.5  837.39   433.1  836.38458.9709833.7599   467.9  833.41471.8309833.7777
   479.5  836.56     499  838.62   523.7  844.61     528  846.34   565.4  867.28
   600.6  881.02   613.4  890.88   630.5  909.07   635.1  911.78   641.9  913.94
#Mann= 4 ,-1,0
       0      .1       0     180     .06       0458.9709    .045       0
471.8309      .1       0
#XS Ineff= 2 , 0
          262.79  856.17
Permanent Ineff=
       F       F
Bank Sta=458.9709,471.8309
XS Rating Curve= 0 ,0
Exp/Cntr(USF)=0,0
Exp/Cntr=0.3,0.1

Type RM Length L Ch R = 1 ,163     ,132.2,140.8,142.3
XS GIS Cut Line= 4
1641485.92002164505481.531295041 1641119.0358692505334.915042043
1640945.22841517 505355.008389331640783.77318594505456.727836057
#Sta/Elev= 30
       0   907.1    18.1  900.61    34.8  893.27    60.5  886.13    85.2  872.93
    95.4  864.92   113.1  863.04   127.6  858.66   138.2  850.67   145.2   844.2
   152.3  841.23   191.2  840.11   212.4  837.93   259.5  839.78   272.4  839.07
   318.4  840.57   541.3  837.14   570.1  835.88     579  832.68   590.6  831.83
  595.24 832.666   602.3  834.82   639.5  837.14   667.8  840.16   687.6  843.43
   701.3  849.11   720.4  855.39   729.9  860.42   748.9   872.2   760.9  876.97
#Mann= 5 ,-1,0
       0      .1       0     190     .06       0     579    .045       0
  595.24     .06       0  690.06      .1       0
Bank Sta=579,595.24
XS Rating Curve= 0 ,0
Exp/Cntr(USF)=0,0
Exp/Cntr=0.3,0.1

Type RM Length L Ch R = 1 ,22      ,,,
XS GIS Cut Line= 4
1641529.70950273505417.9956981851640992.41579475505257.655185681
1640849.48792461505244.5815724931640688.03269538505371.462161649
#Sta/Elev= 30
       0  902.27    25.5  890.32    46.1  884.45    76.9  867.33   131.7   860.4
   141.9  857.65   155.6  850.85   176.1  849.14   233.2  839.57   316.6  842.11
   376.4  841.31   402.1     847   418.7  847.06   485.6  843.27   497.1  841.56
   515.1  834.91   531.5  833.28   619.6  833.57  664.01830.7147   671.7  830.31
   675.8  830.71   729.1  838.25   775.9  840.22   809.1  846.14     846  846.74
   863.3  854.56   876.3  863.22   883.3  865.87   892.7  872.41   909.6  881.23
#Mann= 6 ,-1,0
       0      .1       0     130     .06       0  650.71     .07       0
  664.01    .045       0   675.8     .07       0  744.23     .06       0
Bank Sta=664.01,675.8
XS Rating Curve= 0 ,0
Exp/Cntr(USF)=0,0
Exp/Cntr=0.3,0.1
LCMann Table=0

Chan Stop Cuts=-1
Use User Specified Reach Order=0
Composite Channel Slope=5